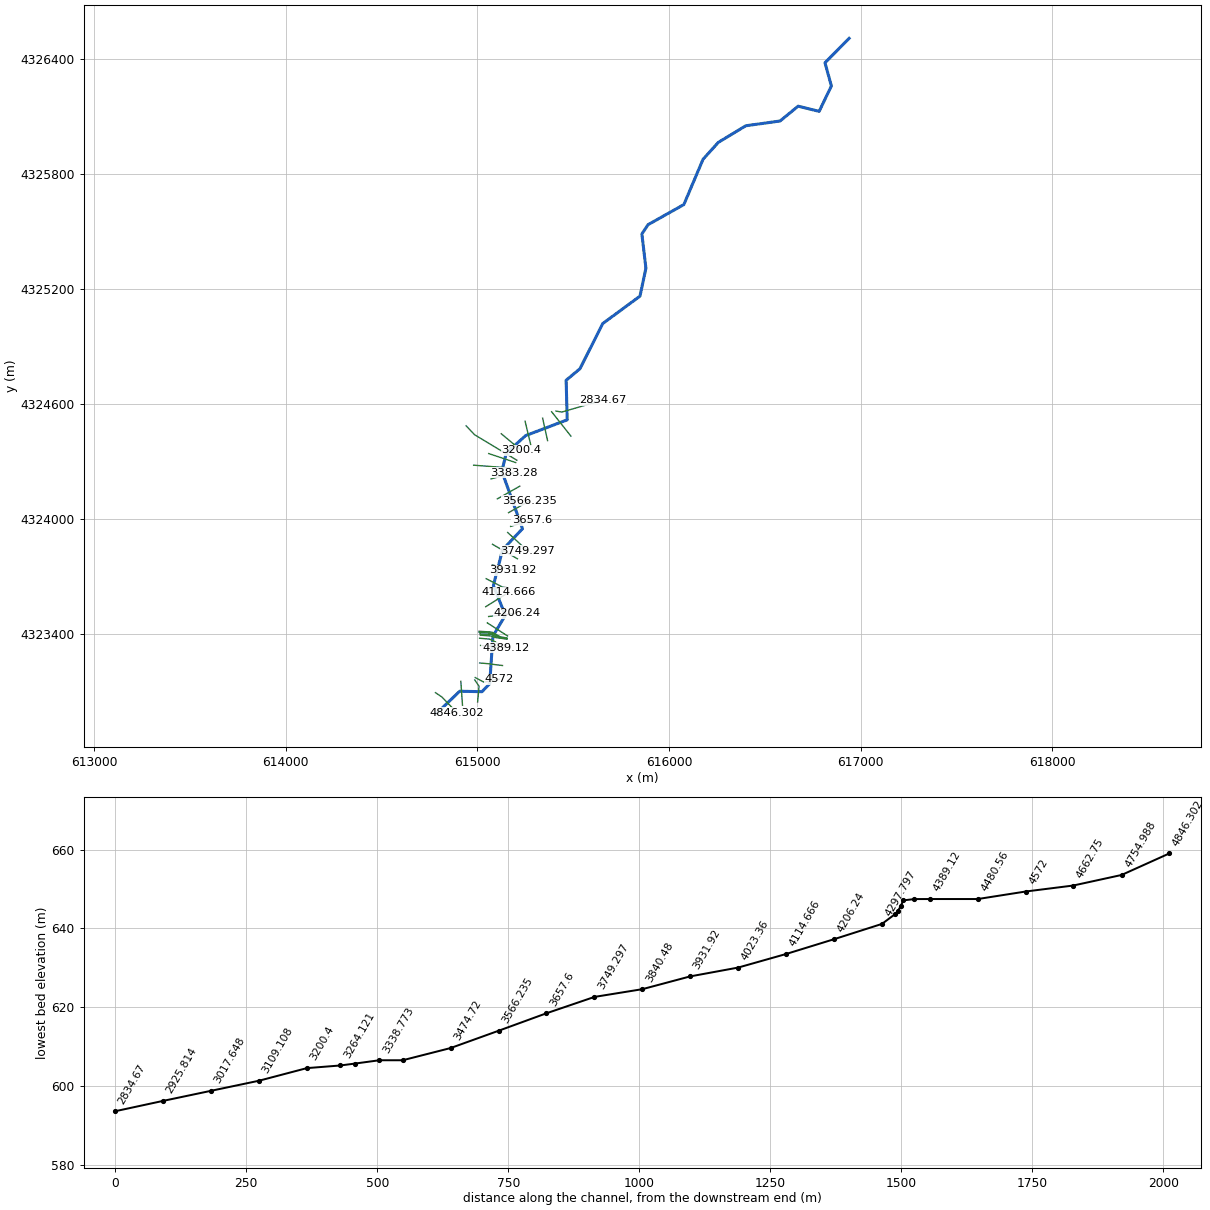
--- ElklickRun.prj (project) ---

Proj Title=ElklickRun
Current Plan=p01
Default Exp/Contr=0.3,0.1
SI Units
Geom File=g01
Flow File=f01
Plan File=p01
Background Map Layer=Google Hybrid
Y Axis Title=Elevation
X Axis Title(PF)=Main Channel Distance
X Axis Title(XS)=Station
BEGIN DESCRIPTION:
September 2018
Tucker County ABFE Study
US Army Corps of Engineers, Pittsburgh District
NAD 1983 UTM 17N (meters)
END DESCRIPTION:
DSS Export Rating Curves= 0
DSS Export Rating Curve Sorted= 0
DSS Export Volume Flow Curves= 0
DXF OffsetX= 0
DXF OffsetY= 0
DXF ScaleX= 1
DXF ScaleY= 10

--- ElklickRun.p01 (plan) ---

Plan Title=ElklickRun_plan
Program Version=5.05
Short Identifier=Plan1_subcritical
Geom File=g01
Flow File=f01
Subcritical Flow
K Sum by GR= 0
Std Step Tol= 0.003
Critical Tol= 0.003
Num of Std Step Trials= 20
Max Error Tol= 0.1
Flow Tol Ratio= 0.001
Split Flow NTrial= 30
Split Flow Tol= 0.006
Split Flow Ratio= 0.02
Log Output Level= 0
Friction Slope Method= 1
Unsteady Friction Slope Method= 2
Unsteady Bridges Friction Slope Method= 1
Parabolic Critical Depth
Global Vel Dist= 0 , 0 , 0
Global Log Level= 0
CheckData=True
Encroach Param=-1 ,0,0, 0
Computation Interval=1MIN
Output Interval=1HOUR
Instantaneous Interval=1HOUR
Mapping Interval=1HOUR
Computation Time Step Use Courant=        0
Computation Time Step Use Time Series=    0
Computation Time Step Count To Double=0
Computation Time Step Max Doubling=0
Computation Time Step Max Halving=0
Computation Time Step Residence Courant=0
Run HTab= 0
Run UNet= 0
Run Sediment= 0
Run PostProcess= 0
Run WQNet= 0
Run RASMapper=-1
UNET Theta= 1
UNET Theta Warmup= 1
UNET ZTol= 0.006
UNET ZSATol= 0.006
UNET MxIter= 20
UNET Max Iter WO Improvement= 0
UNET MaxInSteps= 0
UNET DtIC= 0
UNET DtMin= 0
UNET MaxCRTS= 20
UNET WFStab= 2
UNET SFStab= 1
UNET WFX= 1
UNET SFX= 1
UNET 1D Methodology=Finite Difference
UNET DSS MLevel= 4
UNET Pardiso=0
UNET DZMax Abort= 30
UNET Use Existing IB Tables=-1
UNET Froude Reduction=False
UNET Froude Limit= 0.8
UNET Froude Power= 4
UNET D1 Cores= 0
UNET D2 Coriolis=0
UNET D2 Cores= 0
UNET D2 Theta= 1
UNET D2 Theta Warmup= 1
UNET D2 Z Tol= 0.003
UNET D2 Volume Tol= 0.003
UNET D2 Max Iterations= 20
UNET D2 Equation= 0
UNET D2 RampUpFraction=0.1
UNET D2 TimeSlices= 1
UNET D2 BCVolumeCheck=0
UNET D1D2 MaxIter= 0
UNET D1D2 ZTol=0.003
UNET D1D2 QTol=0.1
UNET D1D2 MinQTol=0.03
Write IC File= 0
Write IC File at Fixed DateTime=0
Write IC File at Sim End=0
Echo Input=False
Echo Parameters=False
Echo Output=False
Write Detailed= 0
HDF Write Warmup=0
HDF Write Time Slices=0
HDF Flush=0
HDF Face Node Velocities=0
HDF Compression= 1
HDF Chunk Size= 1
HDF Spatial Parts= 1
HDF Use Max Rows=0
HDF Fixed Rows= 1
Calibration Method= 0
Calibration Iterations= 20
Calibration Max Change=0.05
Calibration Tolerance=0.2
Calibration Maximum=1.5
Calibration Minimum=0.5
Calibration Optimization Method= 1
WQ AD Non Conservative
WQ ULTIMATE=-1
WQ Max Comp Step=1HOUR
WQ Output Interval=15MIN
WQ Output Selected Increments= 0
WQ Output face flow=0
WQ Output face velocity=0
WQ Output face area=0
WQ Output face dispersion=0
WQ Output cell volume=0
WQ Output cell surface area=0
WQ Output cell continuity=0
WQ Output cumulative cell continuity=0
WQ Output face conc=0
WQ Output face dconc_dx=0
WQ Output face courant=0
WQ Output face peclet=0
WQ Output face adv mass=0
WQ Output face disp mass=0
WQ Output cell mass=0
WQ Output cell source sink temp=0
WQ Output nsm pathways=0
WQ Output nsm derived pathways=0
WQ Output MaxMinRange=-1
WQ Daily Max Min Mean=-1
WQ Daily Range=0
WQ Daily Time=0
WQ Create Restart=0
WQ Fixed Restart=0
WQ System Summary=0
WQ Write To DSS=0
WQ Use Fixed Temperature=0
Sorting and Armoring Iterations= 10
XS Update Threshold= 0.02
Bed Roughness Predictor= 0
Hydraulics Update Threshold= 0.02
Energy Slope Method= 1
Volume Change Method= 1
Sediment Retention Method= 0
XS Weighting Method= 0
Number of US Weighted Cross Sections= 1
Number of DS Weighted Cross Sections= 1
Upstream XS Weight=0
Main XS Weight=1
Downstream XS Weight=0
Number of DS XS's Weighted with US Boundary= 1
Upstream Boundary Weight= 1
Weight of XSs Associated with US Boundary= 0
Number of US XS's Weighted with DS Boundary= 1
Downstream Boundary Weight= 0.5
Weight of XSs Associated with DS Boundary= 0.5
Percentile Method= 0
Sediment Output Level= 4
Mass or Volume Output= 0
Output Increment Type= 1
Profile and TS Output Increment= 1
XS Output Flag= 0
XS Output Increment= 10
Write Gradation File= 0
Read Gradation Hotstart= 0
Write HDF5 File= 1
Write Binary Output= 1
Write DSS Sediment File= 0
SV Curve= 0
Specific Gage Flag= 0

--- ElklickRun.f01 (steady flow) ---

Flow Title=ElklickRun_flow
Program Version=5.05
Number of Profiles= 1
Profile Names=PF 1
River Rch & RM=Elklick Run(Blk),1               ,4846.302
   14.64
River Rch & RM=Elklick Run(Blk),1               ,4480.56
 16.1404
River Rch & RM=Elklick Run(Blk),1               ,3749.297
 18.4907
River Rch & RM=Elklick Run(Blk),1               ,3338.773
 18.8872
River Rch & RM=Elklick Run(Blk),1               ,3264.121
 22.2568
River Rch & RM=Elklick Run(Blk),1               ,2743.164
 25.2018
River Rch & RM=Elklick Run(Blk),1               ,2194.56
  25.938
River Rch & RM=Elklick Run(Blk),1               ,1645.92
 26.9008
River Rch & RM=Elklick Run(Blk),1               ,1371.6
 30.3271
River Rch & RM=Elklick Run(Blk),1               ,91.1701
 34.4896
Boundary for River Rch & Prof#=Elklick Run(Blk),1               , 1
Up Type= 2
Dn Type= 1
Dn Known WS=514.7
DSS Import GetInterval= 0
DSS Import GetPeak= 0
DSS Import FillOption= 0

--- ElklickRun.g01 (geometry) ---

Geom Title=ElklickRun_geometry
Program Version=5.05

River Reach=Elklick Run(Blk),1
Reach XY= 30
     614787.5038    4322986.7041614908.0323374954323102.18006752
     615024.2452    4323099.8262615064.6423294674323141.75478098
615081.5210637294323390.32094627     615146.1605    4323498.3123
     615083.7187     4323653.601     615131.6084    4323839.9011
615235.6801600174323950.18143125     615128.0649     4324249.321
615151.039451244   4324345.15059     615252.3248    4324436.0416
     615468.9528    4324518.2096615463.3999237454324724.70353125
615535.4565902654324784.84893154     615654.3657    4325020.5848
      615848.548    4325163.4819     615879.6035    4325309.1188
     615858.6243     4325488.027     615890.6223    4325536.3963
616077.597917503 4325641.4279825     616177.7487    4325877.7095
     616257.3294    4325965.7021     616400.5361    4326052.4515
      616579.731    4326077.4967     616673.8435    4326154.7288
     616783.5255     4326127.633     616847.2498    4326260.1844
     616813.9406    4326381.3448     616939.9037    4326508.7012

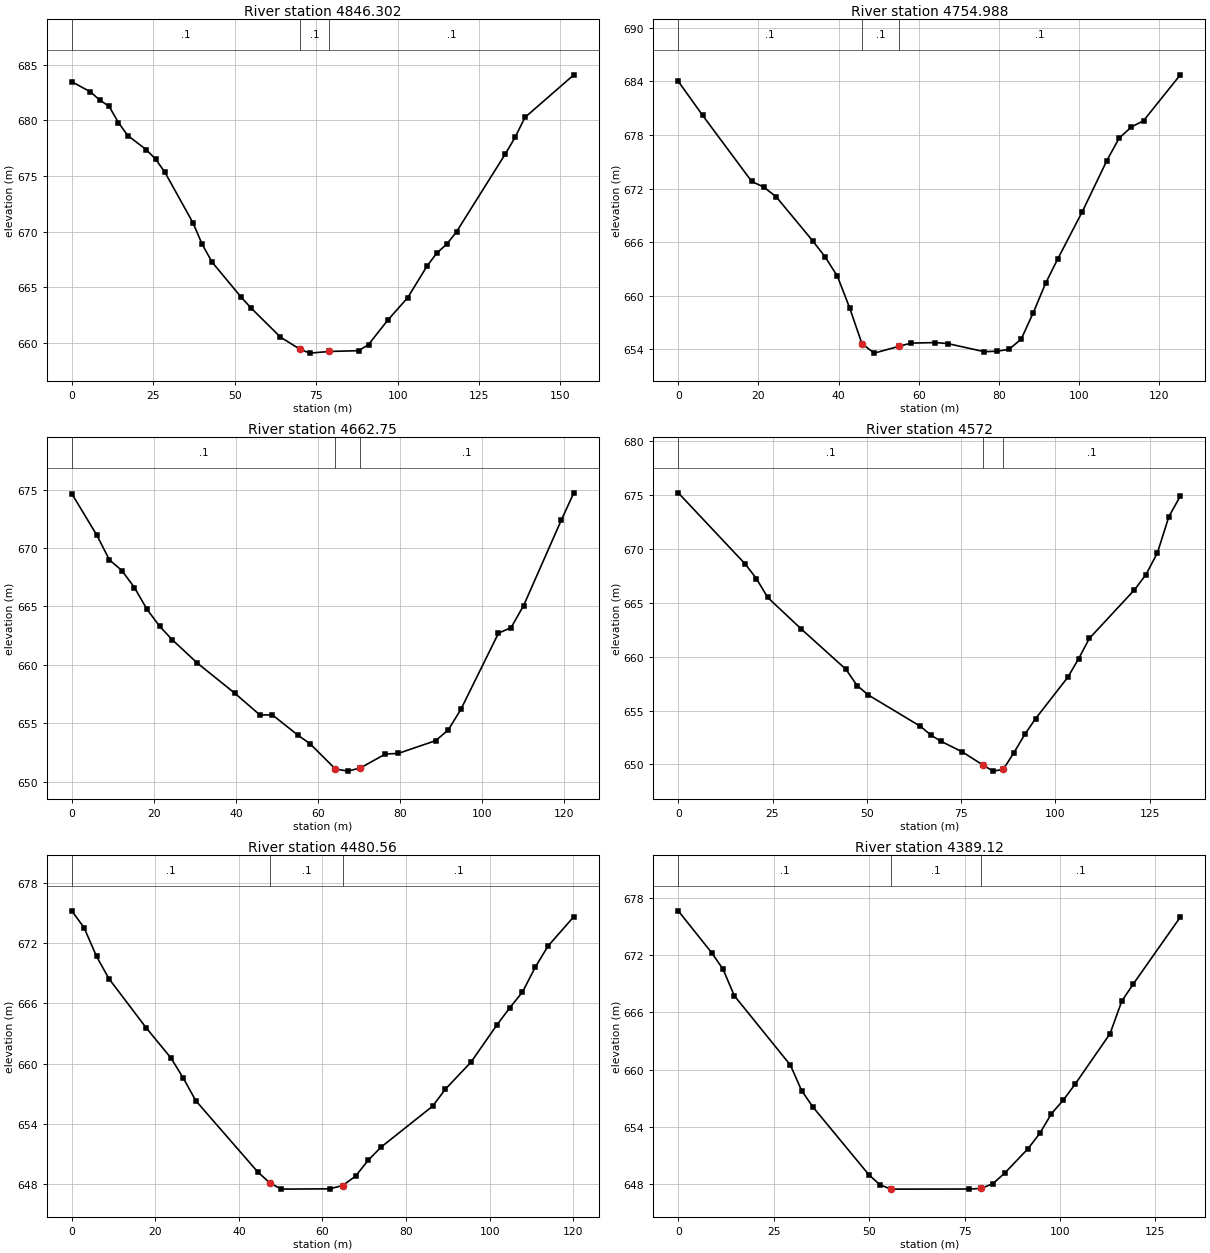
Type RM Length L Ch R = 1 ,4846.302,103.39,91.31,77.61
XS GIS Cut Line= 3
     614781.4633     4323094.799     614814.7602    4323072.5347
     614894.0437     4322990.553
#Sta/Elev= 30
       0  683.48    5.72  682.57    8.58  681.83   11.44  681.27   14.31  679.81
   17.17  678.64   22.89  677.36   25.75  676.51   28.61  675.32   37.19  670.79
   40.05  668.84   43.06  667.25   52.06  664.07   55.06  663.11   64.06   660.5
   70.07   659.4   73.07  659.06   79.07  659.21   88.07  659.28   91.08  659.83
   97.08  662.06  103.08  664.04  109.08  666.91  112.08  668.08  115.09  668.86
  118.09  669.98  133.09  676.99  136.09  678.49   139.1  680.27   154.1   684.1
#Mann= 3 , 0 , 0
       0      .1       0   70.07      .1       0   79.07      .1       0
Bank Sta=70.07,79.07
XS Rating Curve= 0 ,0
Exp/Cntr=0.3,0.1

Type RM Length L Ch R = 1 ,4754.988,95.27,92.24,89.22
XS GIS Cut Line= 2
     614913.8875    4323153.9335      614922.696     4323028.932
#Sta/Elev= 28
       0     684    6.11  680.17   18.34  672.79   21.39  672.15   24.45  671.07
   33.62  666.11   36.68  664.34   39.73  662.18   42.79  658.63   45.85  654.64
    48.9  653.58   55.01  654.33   58.07   654.7   64.18  654.76   67.24  654.65
   76.41  653.74   79.47  653.79   82.52     654   85.58  655.13   88.63  658.12
   91.69   661.4   94.75  664.15  100.86  669.42  106.97  675.12  110.03  677.63
  113.09  678.88  116.14  679.59  125.31  684.72
#Mann= 3 , 0 , 0
       0      .1       0   45.85      .1       0   55.01      .1       0
Bank Sta=45.85,55.01
XS Rating Curve= 0 ,0
Exp/Cntr=0.3,0.1

Type RM Length L Ch R = 1 ,4662.75 ,58.69,90.75,124.92
XS GIS Cut Line= 3
     614986.6481    4323161.0773     615009.1468    4323128.3534
     615001.5454    4323046.0943
#Sta/Elev= 27
       0  674.65    6.11  671.09    9.16  668.99   12.22  668.06   15.27  666.61
   18.33  664.75   21.38  663.31   24.44  662.16   30.55  660.16   39.71  657.57
   45.83  655.71   48.89  655.71   55.01     654   58.07  653.24   64.19  651.09
   67.25   650.9   70.31  651.17   76.43  652.37   79.49  652.41   88.67  653.51
   91.73  654.43   94.79  656.18  103.96  662.71  107.02  663.18  110.08  665.07
  119.26  672.38  122.32  674.72
#Mann= 3 , 0 , 0
       0      .1       0   64.19      .1       0   70.31      .1       0
Bank Sta=64.19,70.31
XS Rating Curve= 0 ,0
Exp/Cntr=0.3,0.1

Type RM Length L Ch R = 1 ,4572    ,95.58,91.44,85.94
XS GIS Cut Line= 6
     614989.1285    4323173.5789     615033.6296    4323149.9136
     615058.2934    4323153.3538     615068.9254    4323155.6685
     615093.4256    4323163.4074     615114.6578    4323164.7231
#Sta/Elev= 26
       0  675.18   17.79  668.57   20.75  667.22   23.72  665.48   32.61  662.56
   44.47  658.82   47.44  657.31    50.4  656.44   64.24  653.53      67  652.72
   69.77  652.13    75.3  651.17   80.75  649.96   83.47  649.38   86.19  649.54
   89.04   651.1    91.9  652.78   94.75  654.24  103.31  658.08  106.17  659.79
  109.02  661.68     121  666.19  124.04   667.6  127.07  669.61  130.11  672.97
  133.15  674.88
#Mann= 3 , 0 , 0
       0      .1       0   80.75      .1       0   86.19      .1       0
Bank Sta=80.75,86.19
XS Rating Curve= 0 ,0
Exp/Cntr=0.3,0.1

Type RM Length L Ch R = 1 ,4480.56 ,91.8,91.44,94.95
XS GIS Cut Line= 4
     615011.9559    4323249.6976     615059.2359    4323245.6925
     615067.2713    4323244.2554     615131.3424    4323236.4176
#Sta/Elev= 25
       0  675.23    2.97  673.53    5.93  670.68     8.9  668.46   17.79  663.57
   23.72  660.56   26.69  658.55   29.66   656.3   44.48   649.2   47.45  648.07
   50.17  647.47   61.76   647.5   64.83  647.83   67.91  648.76   70.98  650.37
   74.05  651.67   86.35  655.74   89.42  657.44   95.57  660.15  101.72  663.83
  104.79  665.54  107.87  667.13  110.94  669.62  114.01  671.73  120.16  674.65
#Mann= 3 , 0 , 0
       0      .1       0   47.45      .1       0   64.83      .1       0
Bank Sta=47.45,64.83
XS Rating Curve= 0 ,0
Exp/Cntr=0.3,0.1

Type RM Length L Ch R = 1 ,4389.12 ,39.68,29.34,20.43
XS GIS Cut Line= 4
     615016.8429    4323341.2298     615066.6307    4323337.2608
     615086.5238     4323333.703     615147.7907    4323330.2125
#Sta/Elev= 23
       0  676.64    8.81  672.22   11.75  670.51   14.69  667.74   29.38  660.47
   32.32   657.8   35.26  656.09   49.95  648.97   52.83  647.93   55.72  647.47
   76.29  647.48   79.36  647.54   82.43  648.05    85.5  649.14   91.63  651.71
    94.7  653.31   97.77  655.38  100.84  656.79  103.91  658.44  113.11  663.76
  116.18  667.17  119.25     669  131.52  675.98
#Mann= 3 , 0 , 0
       0      .1       0   55.72      .1       0   79.36      .1       0
Bank Sta=55.72,79.36
XS Rating Curve= 0 ,0
Exp/Cntr=0.3,0.1

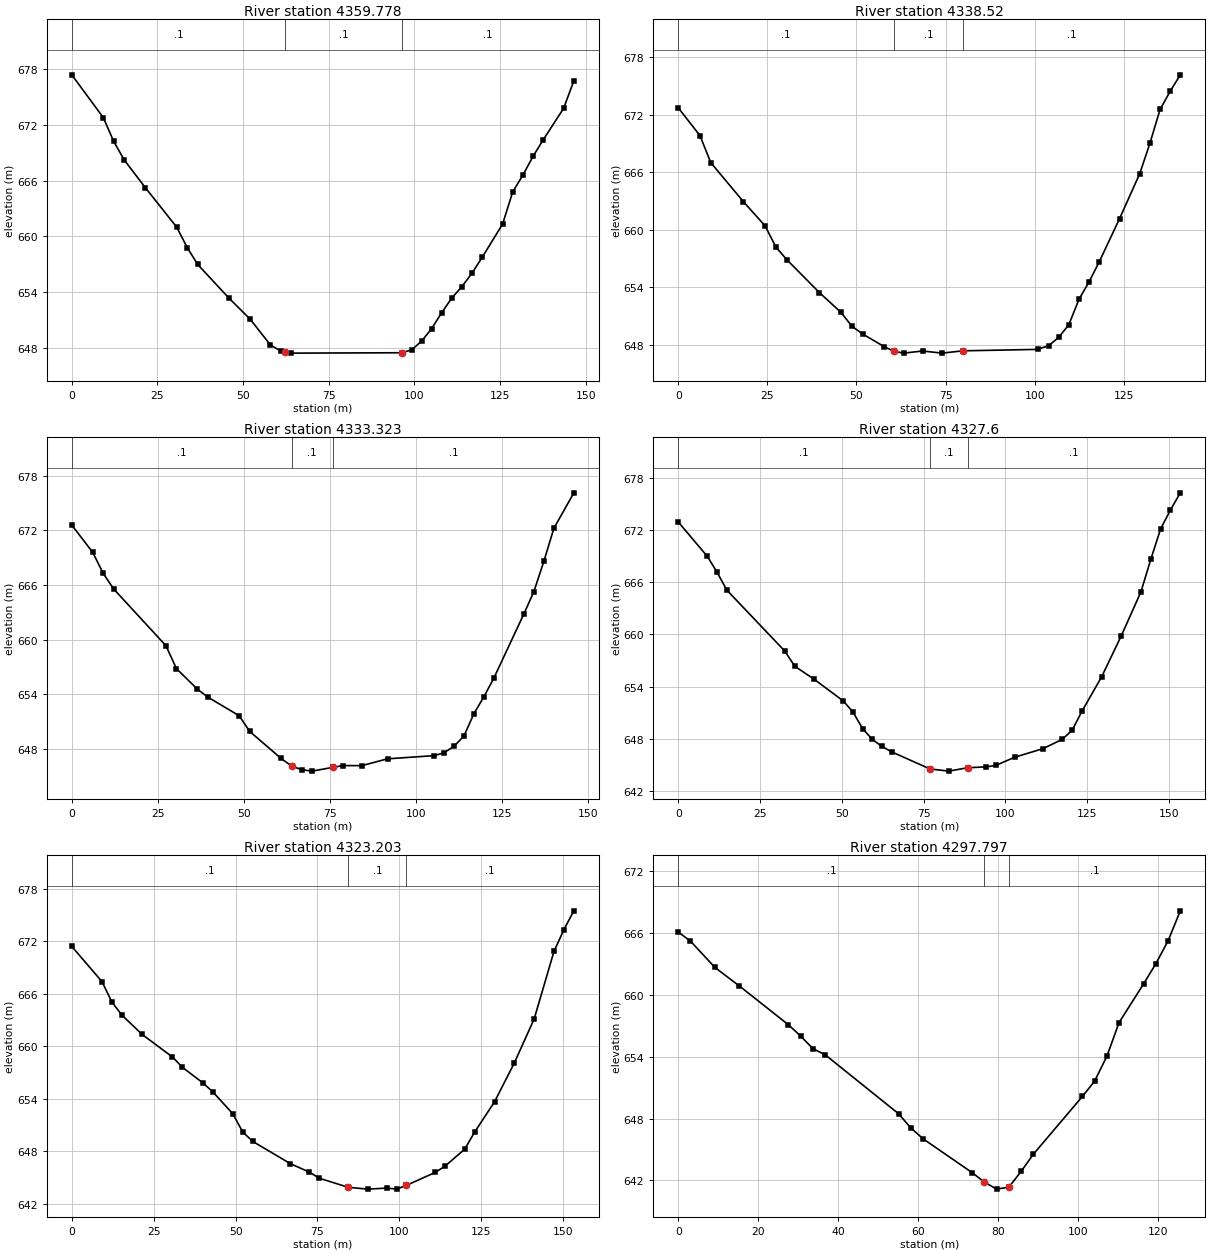
Type RM Length L Ch R = 1 ,4359.778,19.14,21.26,32.12
XS GIS Cut Line= 5
      615011.817    4323378.7367     615063.6755    4323374.2917
     615093.0972    4323360.3217     615111.7239    4323346.3517
     615150.2473       4323343.6
#Sta/Elev= 30
       0  677.37    9.19  672.78   12.25  670.21   15.31  668.22   21.43  665.26
   30.62     661   33.68  658.81   36.74  656.99   45.93  653.35   52.05  651.11
   57.97  648.34   60.93   647.7   62.33  647.59   63.89  647.46   96.26   647.5
   99.17  647.81  102.08  648.74  104.99  650.08   107.9  651.77  110.87  653.37
  113.84   654.6  116.81  656.06  119.79  657.77  125.73  661.33   128.7  664.81
  131.67   666.6  134.64  668.63  137.61   670.4  143.55  673.78  146.52  676.73
#Mann= 3 , 0 , 0
       0      .1       0   62.33      .1       0   96.26      .1       0
Bank Sta=62.33,96.26
XS Rating Curve= 0 ,0
Exp/Cntr=0.3,0.1

Type RM Length L Ch R = 1 ,4338.52 ,8.02,5.2,2.68
XS GIS Cut Line= 6
     615015.8377    4323394.7107     615073.5169    4323390.2128
     615085.8466    4323385.0534     615099.6578    4323381.4022
     615117.9141    4323379.3384     615154.5061    4323374.0203
#Sta/Elev= 30
       0  672.75    6.09  669.85    9.13  667.02   18.27  662.95   24.36  660.42
    27.4  658.21   30.45  656.89   39.58  653.46   45.67  651.38   48.72  649.94
   51.76  649.12   57.85  647.79   60.53  647.33    63.2  647.13   68.55  647.35
   74.08  647.13   79.79  647.37  100.82  647.52  103.88   647.9  106.72  648.77
  109.57  650.09  112.41  652.74  115.26  654.58   118.1  656.66  123.79  661.16
  129.48  665.88  132.32  669.04  135.17  672.57  138.01  674.48  140.85  676.19
#Mann= 3 , 0 , 0
       0      .1       0   60.53      .1       0   79.79      .1       0
Bank Sta=60.53,79.79
XS Rating Curve= 0 ,0
Exp/Cntr=0.3,0.1

Type RM Length L Ch R = 1 ,4333.323,6.39,5.72,1.77
XS GIS Cut Line= 6
     615013.1125    4323401.6561     615076.8507    4323398.2429
     615092.3289    4323389.1942     615101.6951    4323385.8604
     615117.4908    4323381.4948     615154.7442    4323375.5284
#Sta/Elev= 30
       0  672.57    6.08  669.59    9.12  667.28   12.16  665.57   27.36  659.34
   30.39  656.84   36.47  654.58   39.51  653.71   48.63  651.66   51.67  649.95
   60.79  646.98   63.83  646.15   66.82  645.74   69.81  645.59   75.78     646
   78.77   646.2   84.24  646.19    91.7  646.94   105.3  647.29   108.1   647.6
     111  648.31   113.9  649.44   116.8  651.89   119.7  653.75  122.61  655.81
  131.31  662.83  134.21  665.28  137.12  668.61  140.02  672.22  145.82  676.11
#Mann= 3 , 0 , 0
       0      .1       0   63.83      .1       0   75.78      .1       0
Bank Sta=63.83,75.78
XS Rating Curve= 0 ,0
Exp/Cntr=0.3,0.1

Type RM Length L Ch R = 1 ,4327.6  ,4.36,4.4,4.44
XS GIS Cut Line= 4
     615008.2505    4323410.5186     615079.1589    4323404.1685
     615116.7828    4323382.9489      615155.412    4323376.9164
#Sta/Elev= 30
       0  672.92     8.9  668.96   11.87  667.15   14.83   665.1   32.63  658.07
    35.6  656.36   41.53  654.86   50.43  652.37   53.39  651.11   56.36  649.19
   59.33  647.95   62.29  647.14   65.26  646.52   76.95  644.56   82.71  644.31
   88.47   644.7   94.23   644.8   97.11  644.97  102.87  645.91  111.51  646.89
  117.39  647.96   120.4  648.99  123.41  651.18  129.42  655.13  135.44  659.85
  141.45   664.9  144.46  668.63  147.47  672.13  150.48   674.3  153.48  676.26
#Mann= 3 , 0 , 0
       0      .1       0   76.95      .1       0   88.47      .1       0
Bank Sta=76.95,88.47
XS Rating Curve= 0 ,0
Exp/Cntr=0.3,0.1

Type RM Length L Ch R = 1 ,4323.203,26.49,25.41,24.32
XS GIS Cut Line= 5
     615009.0908    4323415.2424     615064.2565    4323411.8028
     615078.4117    4323409.5539     615119.6868    4323386.4028
     615155.4057    4323379.7882
#Sta/Elev= 30
       0  671.43    9.21  667.41   12.28  665.05   15.35  663.55   21.49  661.36
   30.71  658.79   33.78   657.6   39.92  655.85   42.99  654.82   49.13   652.3
    52.2   650.2   55.27  649.12   66.74  646.58   72.56  645.61   75.52  644.92
   84.39  643.88   90.31  643.67   96.23  643.79   99.18  643.67  102.14   644.1
  111.01  645.59  113.97  646.31  119.96  648.24  122.98   650.2  129.04  653.65
  135.09   658.1  141.15  663.14   147.2  670.86  150.23  673.36  153.26   675.5
#Mann= 3 , 0 , 0
       0      .1       0   84.39      .1       0  102.14      .1       0
Bank Sta=84.39,102.14
XS Rating Curve= 0 ,0
Exp/Cntr=0.3,0.1

Type RM Length L Ch R = 1 ,4297.797,79.71,91.56,103.4
XS GIS Cut Line= 2
     615052.1877    4323458.8973     615157.5686    4323390.6087
#Sta/Elev= 25
       0   666.1    3.06  665.22    9.19  662.66   15.31  660.86   27.56   657.1
   30.63     656   33.69  654.78   36.75  654.19   55.13  648.46   58.19  647.08
   61.25  646.03   73.51  642.75   76.57  641.83   79.63  641.15   82.69  641.34
   85.76  642.87   88.82  644.54  101.07  650.14  104.13  651.63   107.2  654.04
  110.26  657.32  116.38  661.07  119.45  663.03  122.51  665.25  125.57  668.16
#Mann= 3 , 0 , 0
       0      .1       0   76.57      .1       0   82.69      .1       0
Bank Sta=76.57,82.69
XS Rating Curve= 0 ,0
Exp/Cntr=0.3,0.1

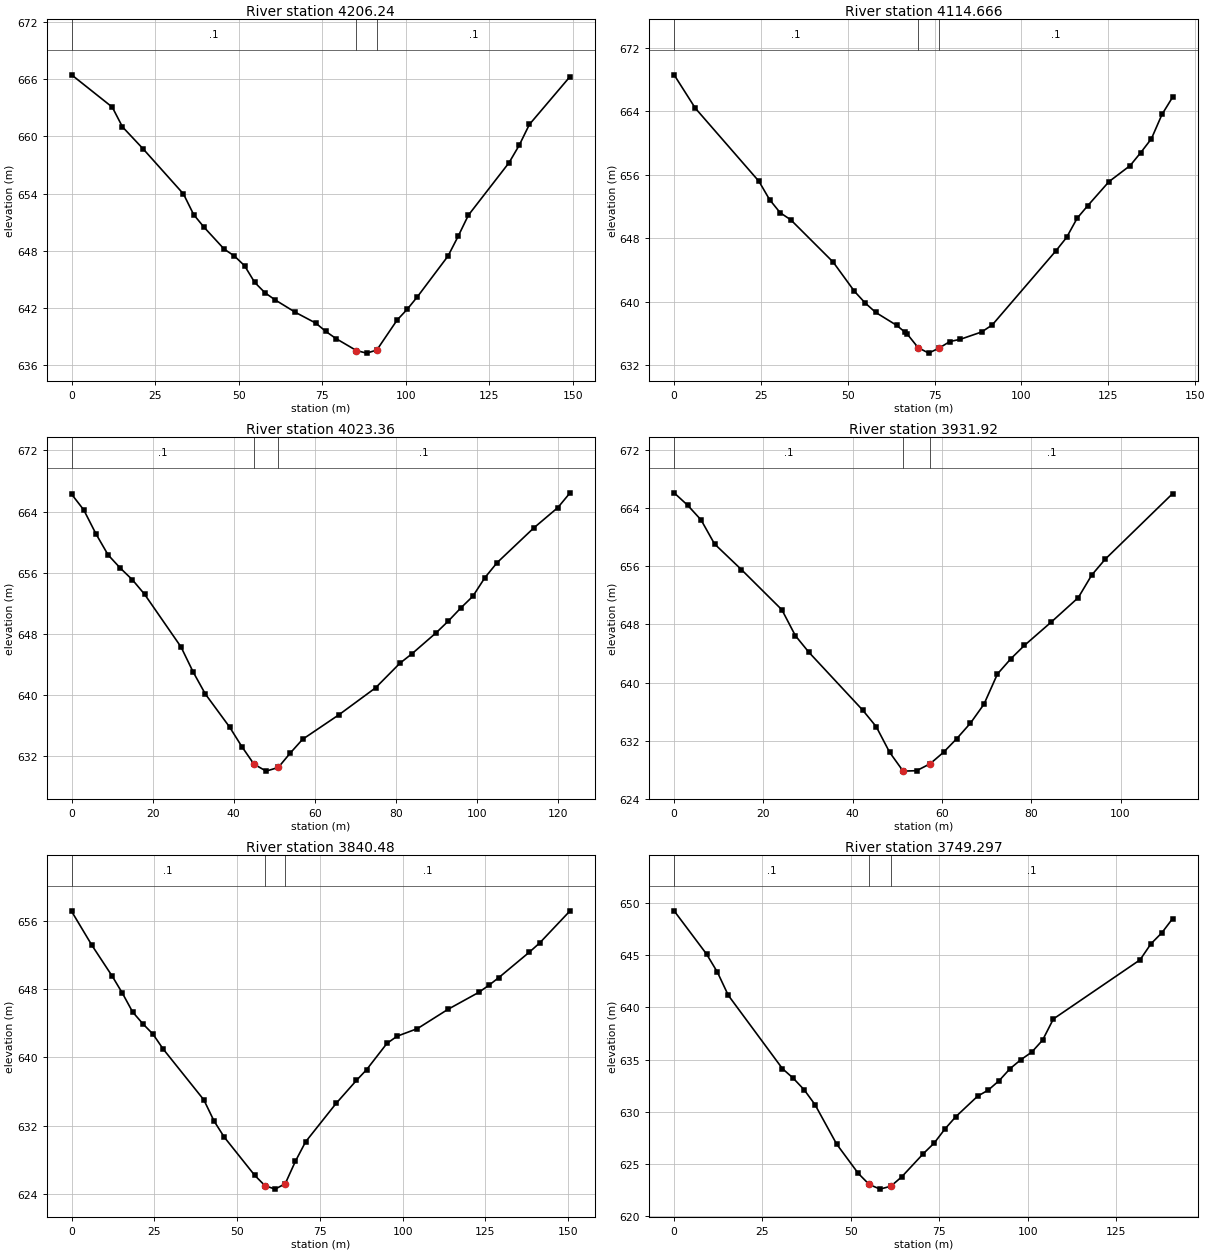
Type RM Length L Ch R = 1 ,4206.24 ,83.9,91.57,99.25
XS GIS Cut Line= 2
     615059.0139    4323492.0879     615207.2678    4323509.1939
#Sta/Elev= 30
       0  666.45   12.18  663.06   15.23  660.99   21.32  658.72    33.5  653.95
   36.55  651.79   39.59  650.49   45.68  648.17   48.73  647.45   51.78  646.43
   54.82  644.68   57.87   643.6   60.91  642.85      67  641.54    73.1  640.41
   76.14  639.53   79.19  638.78   85.28  637.53   88.32  637.26   91.37  637.58
   97.46  640.73  100.51  641.87  103.55  643.18  112.69  647.44  115.74  649.52
  118.78  651.72  130.96  657.23  134.01  659.06  137.05  661.24  149.24  666.27
#Mann= 3 , 0 , 0
       0      .1       0   85.28      .1       0   91.37      .1       0
Bank Sta=85.28,91.37
XS Rating Curve= 0 ,0
Exp/Cntr=0.3,0.1

Type RM Length L Ch R = 1 ,4114.666,109.24,91.31,73.37
XS GIS Cut Line= 2
     615043.8533    4323543.2224     615165.5619    4323619.2902
#Sta/Elev= 30
       0  668.59    6.11  664.38   24.43  655.16   27.48  652.86   30.54   651.2
   33.59  650.31   45.81  644.97   51.91   641.3   54.97  639.84   58.02  638.64
   64.13  636.99   66.46  636.14   67.18  635.87   70.24   634.2   73.29   633.5
   76.34  634.15    79.4  634.96   82.45  635.25   88.56  636.17   91.61  637.06
  109.93   646.4  112.99  648.08  116.04  650.51  119.09  652.09   125.2  655.12
  131.31  657.15  134.36  658.79  137.42  660.53  140.47   663.6  143.52  665.77
#Mann= 3 , 0 , 0
       0      .1       0   70.24      .1       0   76.34      .1       0
Bank Sta=70.24,76.34
XS Rating Curve= 0 ,0
Exp/Cntr=0.3,0.1

Type RM Length L Ch R = 1 ,4023.36 ,87.51,91.44,95.37
XS GIS Cut Line= 3
     615046.2273    4323689.3656     615131.7007    4323645.5863
     615158.4925    4323642.0862
#Sta/Elev= 30
       0  666.27       3  664.22       6   661.1       9  658.34      12  656.62
   15.01  655.08   18.01  653.19   27.01   646.3   30.01  643.02   33.01  640.15
   39.01  635.82   42.01  633.28   45.02  630.97   48.02  630.06   51.02  630.54
   54.02  632.45   57.02  634.22   66.02  637.44   75.03  640.95   81.03  644.16
   84.03  645.41   90.03  648.17   93.03   649.7   96.03  651.37   99.04  652.92
  102.04  655.37  105.04  657.32  114.05  661.84  120.05  664.53  123.05  666.45
#Mann= 3 , 0 , 0
       0      .1       0   45.02      .1       0   51.02      .1       0
Bank Sta=45.02,51.02
XS Rating Curve= 0 ,0
Exp/Cntr=0.3,0.1

Type RM Length L Ch R = 1 ,3931.92 ,96.44,91.44,86.39
XS GIS Cut Line= 2
     615078.0684    4323761.1335     615186.3921    4323734.0525
#Sta/Elev= 26
       0  666.11    3.02  664.41    6.04  662.38    9.05  659.08   15.09  655.54
   24.14  650.02   27.16  646.46   30.18  644.18   42.25  636.21   45.27  633.94
   48.28  630.41    51.3  627.82   54.32  627.88   57.34  628.83   60.36  630.42
   63.33   632.3   66.39  634.43   69.41  637.03   72.43  641.19   75.44  643.29
   78.46  645.11    84.5  648.34   90.53  651.69   93.55   654.8   96.57  656.98
  111.66     666
#Mann= 3 , 0 , 0
       0      .1       0    51.3      .1       0   57.34      .1       0
Bank Sta=51.3,57.34
XS Rating Curve= 0 ,0
Exp/Cntr=0.3,0.1

Type RM Length L Ch R = 1 ,3840.48 ,95.29,91.18,87.12
XS GIS Cut Line= 2
     615079.1263    4323868.8849     615209.3193    4323793.2887
#Sta/Elev= 30
       0  657.12    6.14  653.14   12.29  649.51   15.36  647.52   18.43  645.33
   21.51  643.95   24.58  642.73   27.65  640.99   39.94  635.03   43.01  632.56
   46.09  630.67    55.3  626.19   58.38  624.98   61.45  624.57   64.52   625.2
   67.59  627.83   70.67  630.11   79.88  634.61   86.03  637.31    89.1  638.57
   95.25  641.65   98.32  642.49  104.46  643.38  113.68  645.64   122.9  647.61
  125.97  648.44  129.04  649.36  138.26  652.34  141.33   653.4  150.55  657.18
#Mann= 3 , 0 , 0
       0      .1       0   58.38      .1       0   64.52      .1       0
Bank Sta=58.38,64.52
XS Rating Curve= 0 ,0
Exp/Cntr=0.3,0.1

Type RM Length L Ch R = 1 ,3749.297,73.19,91.7,109.47
XS GIS Cut Line= 2
     615158.3123    4323930.5291     615261.9366    4323834.8942
#Sta/Elev= 30
       0  649.25     9.2   645.1   12.26  643.37   15.33  641.16   30.65  634.14
   33.72  633.22   36.79  632.12   39.85   630.7   45.98  626.92   52.11  624.11
   55.18  623.06   58.24  622.61   61.31  622.89   64.37  623.78   70.51  626.01
   73.57  627.02   76.64  628.38    79.7  629.55   85.83   631.5    88.9   632.1
   91.96     633   95.03  634.14   98.09     635  101.16  635.72  104.23  636.87
  107.29   638.9  131.81  644.56  134.88  646.09  137.95  647.14  141.01   648.5
#Mann= 3 , 0 , 0
       0      .1       0   55.18      .1       0   61.31      .1       0
Bank Sta=55.18,61.31
XS Rating Curve= 0 ,0
Exp/Cntr=0.3,0.1

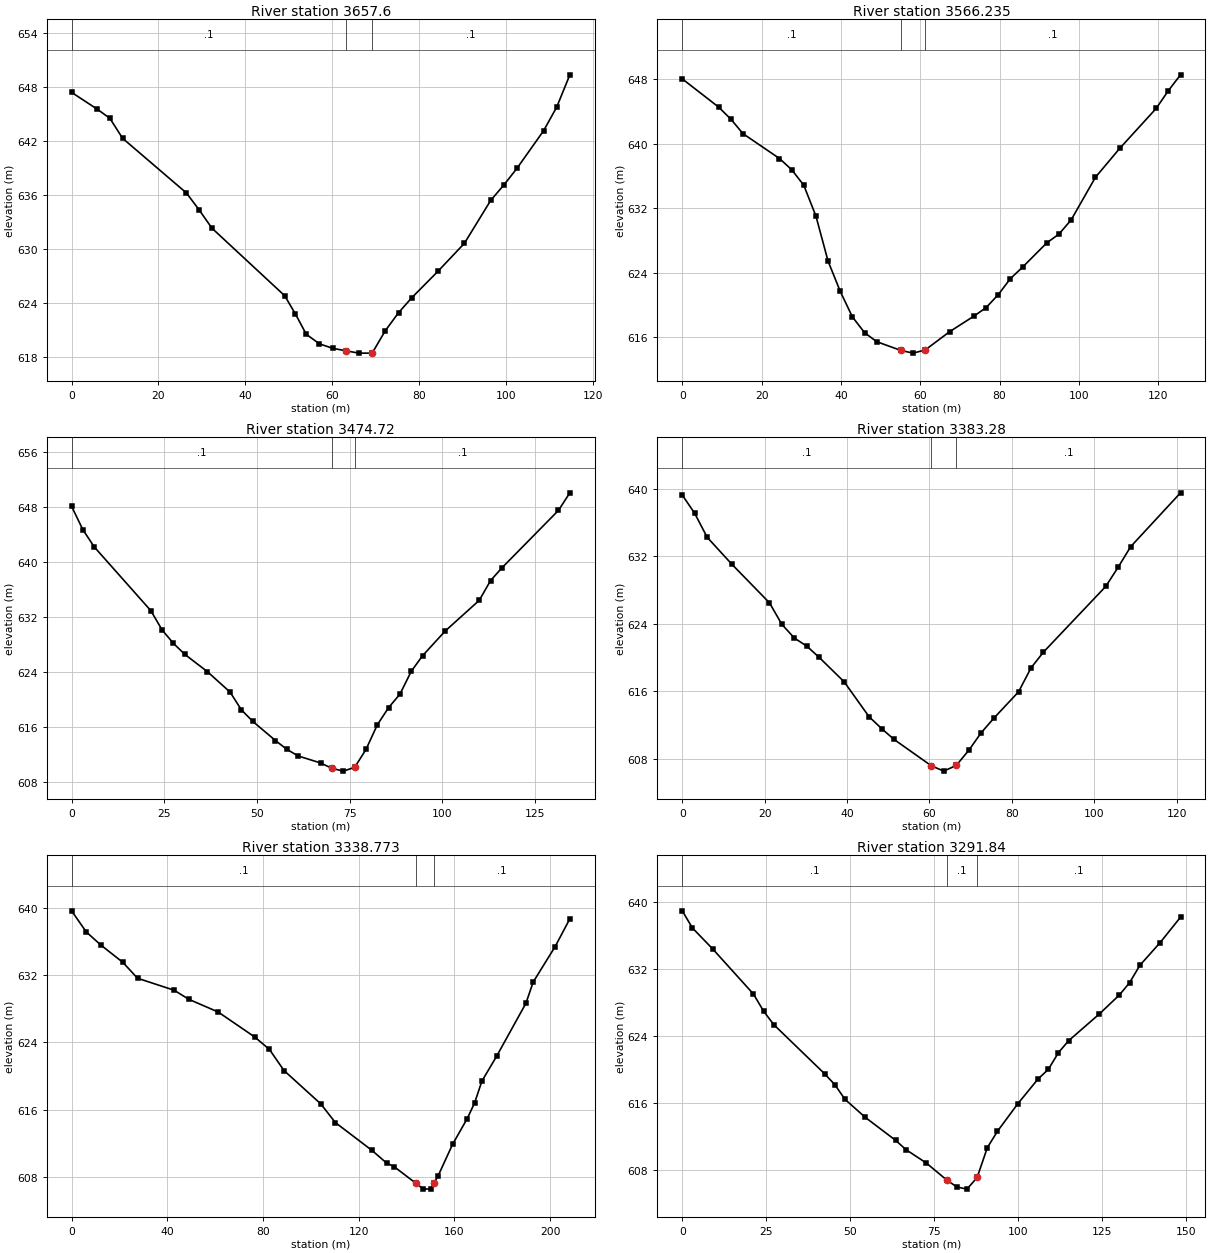
Type RM Length L Ch R = 1 ,3657.6  ,85.34,91.36,98.12
XS GIS Cut Line= 4
     615173.6397    4323962.0397     615215.7617    4323974.9394
     615225.5286    4323976.9243     615283.8794    4323993.5495
#Sta/Elev= 26
       0  647.44    5.87  645.58    8.81  644.56   11.75  642.33   26.43  636.26
   29.37  634.37   32.31  632.34   49.04  624.84   51.53   622.8   54.02  620.55
   57.05  619.48   60.09  618.99   63.12  618.71   66.15  618.45   69.19  618.45
   72.22  620.95   75.26  622.94   78.29   624.6   84.36  627.56   90.42  630.66
   96.49  635.44   99.52  637.15  102.56  639.02  108.63  643.16  111.66  645.79
  114.69  649.39
#Mann= 3 , 0 , 0
       0      .1       0   63.12      .1       0   69.19      .1       0
Bank Sta=63.12,69.19
XS Rating Curve= 0 ,0
Exp/Cntr=0.3,0.1

Type RM Length L Ch R = 1 ,3566.235,91.57,91.52,91.55
XS GIS Cut Line= 2
     615162.8314    4324033.8402     615272.2424     4324095.612
#Sta/Elev= 30
       0  648.03    9.19  644.52   12.26  643.03   15.32  641.23   24.52  638.15
   27.58  636.77   30.64  634.84   33.71  631.01   36.77  625.42   39.84  621.67
    42.9  618.51   45.97  616.55   49.03  615.43   55.16  614.34   58.23  614.01
   61.29  614.41   67.42  616.67   73.55   618.6   76.61  619.65   79.68  621.26
   82.74  623.25   85.81  624.67   91.93  627.69      95  628.78   98.06  630.53
  104.19  635.82  110.32  639.41  119.52  644.37  122.58  646.57  125.64  648.53
#Mann= 3 , 0 , 0
       0      .1       0   55.16      .1       0   61.29      .1       0
Bank Sta=55.16,61.29
XS Rating Curve= 0 ,0
Exp/Cntr=0.3,0.1

Type RM Length L Ch R = 1 ,3474.72 ,95.76,91.44,87.12
XS GIS Cut Line= 2
     615104.4999    4324105.9554     615221.4887    4324172.0869
#Sta/Elev= 30
       0  648.11    3.05  644.71    6.11  642.21   21.38  632.94   24.43  630.13
   27.49  628.18   30.54  626.59   36.65  624.07   42.76   621.1   45.81  618.52
   48.87  616.85   54.98  614.07   58.03   612.8   61.08  611.83   67.19   610.8
   70.25  610.02    73.3  609.62   76.36  610.17   79.41  612.77   82.46  616.35
   85.52  618.86   88.57  620.81   91.63  624.14   94.68   626.4  100.79  629.99
  109.95  634.44  113.01  637.31  116.06  639.16  131.33  647.52  134.39  650.07
#Mann= 3 , 0 , 0
       0      .1       0   70.25      .1       0   76.36      .1       0
Bank Sta=70.25,76.36
XS Rating Curve= 0 ,0
Exp/Cntr=0.3,0.1

Type RM Length L Ch R = 1 ,3383.28 ,50.28,44.51,38.73
XS GIS Cut Line= 2
     615071.7549    4324210.0993     615188.5945    4324241.2566
#Sta/Elev= 26
       0  639.24    3.02  637.07    6.05  634.23   12.09  631.01   21.16  626.47
   24.18  623.91   27.21  622.29   30.23  621.33   33.25  619.99    39.3   617.1
   45.35  612.96   48.37  611.57   51.39  610.28   60.46  607.15   63.48  606.52
   66.51   607.2   69.53  608.98   72.55  611.07   75.58  612.77   81.62  615.92
   84.65  618.76   87.67  620.63  102.78  628.41  105.81   630.7  108.83  633.12
  120.92   639.5
#Mann= 3 , 0 , 0
       0      .1       0   60.46      .1       0   66.51      .1       0
Bank Sta=60.46,66.51
XS Rating Curve= 0 ,0
Exp/Cntr=0.3,0.1

Type RM Length L Ch R = 1 ,3338.773,51.13,46.93,42.74
XS GIS Cut Line= 2
     614980.7378    4324281.6214     615188.3829    4324265.7119
#Sta/Elev= 30
       0  639.67    6.13  637.16   12.25  635.59   21.44  633.53   27.56  631.64
   42.88  630.21      49  629.13   61.25  627.62   76.56  624.64   82.69  623.16
   88.81  620.64  104.13  616.68  110.25  614.45  125.56  611.13  131.69  609.62
  134.75  609.21  143.94  607.21     147  606.54  150.07  606.52   151.5  607.24
  153.13  608.06  159.25  611.86  165.38  614.93  168.44  616.78   171.5  619.39
  177.63  622.34  189.88  628.65  192.94  631.19  202.13  635.42  208.25  638.72
#Mann= 3 , 0 , 0
       0      .1       0  143.94      .1       0   151.5      .1       0
Bank Sta=143.94,151.5
XS Rating Curve= 0 ,0
Exp/Cntr=0.3,0.1

Type RM Length L Ch R = 1 ,3291.84 ,31.5,27.72,23.94
XS GIS Cut Line= 2
      615059.404     4324342.275     615200.0965    4324295.3777
#Sta/Elev= 30
       0  638.91    3.03  636.86    9.08  634.35   21.19  628.97   24.21  626.93
   27.24  625.32   42.37  619.45    45.4  618.15   48.43   616.4   54.48  614.24
   63.56  611.48   66.58  610.39   72.64  608.79   78.69  606.77   81.72  605.93
   84.74  605.67   87.77  607.06    90.8  610.62   93.82  612.58   99.88  615.87
  105.93  618.84  108.96  619.97  111.98  621.98  115.01   623.4  124.09  626.57
  130.14  628.87  133.17  630.34   136.2   632.4  142.25  635.12   148.3  638.15
#Mann= 3 , 0 , 0
       0      .1       0   78.69      .1       0   87.77      .1       0
Bank Sta=78.69,87.77
XS Rating Curve= 0 ,0
Exp/Cntr=0.3,0.1

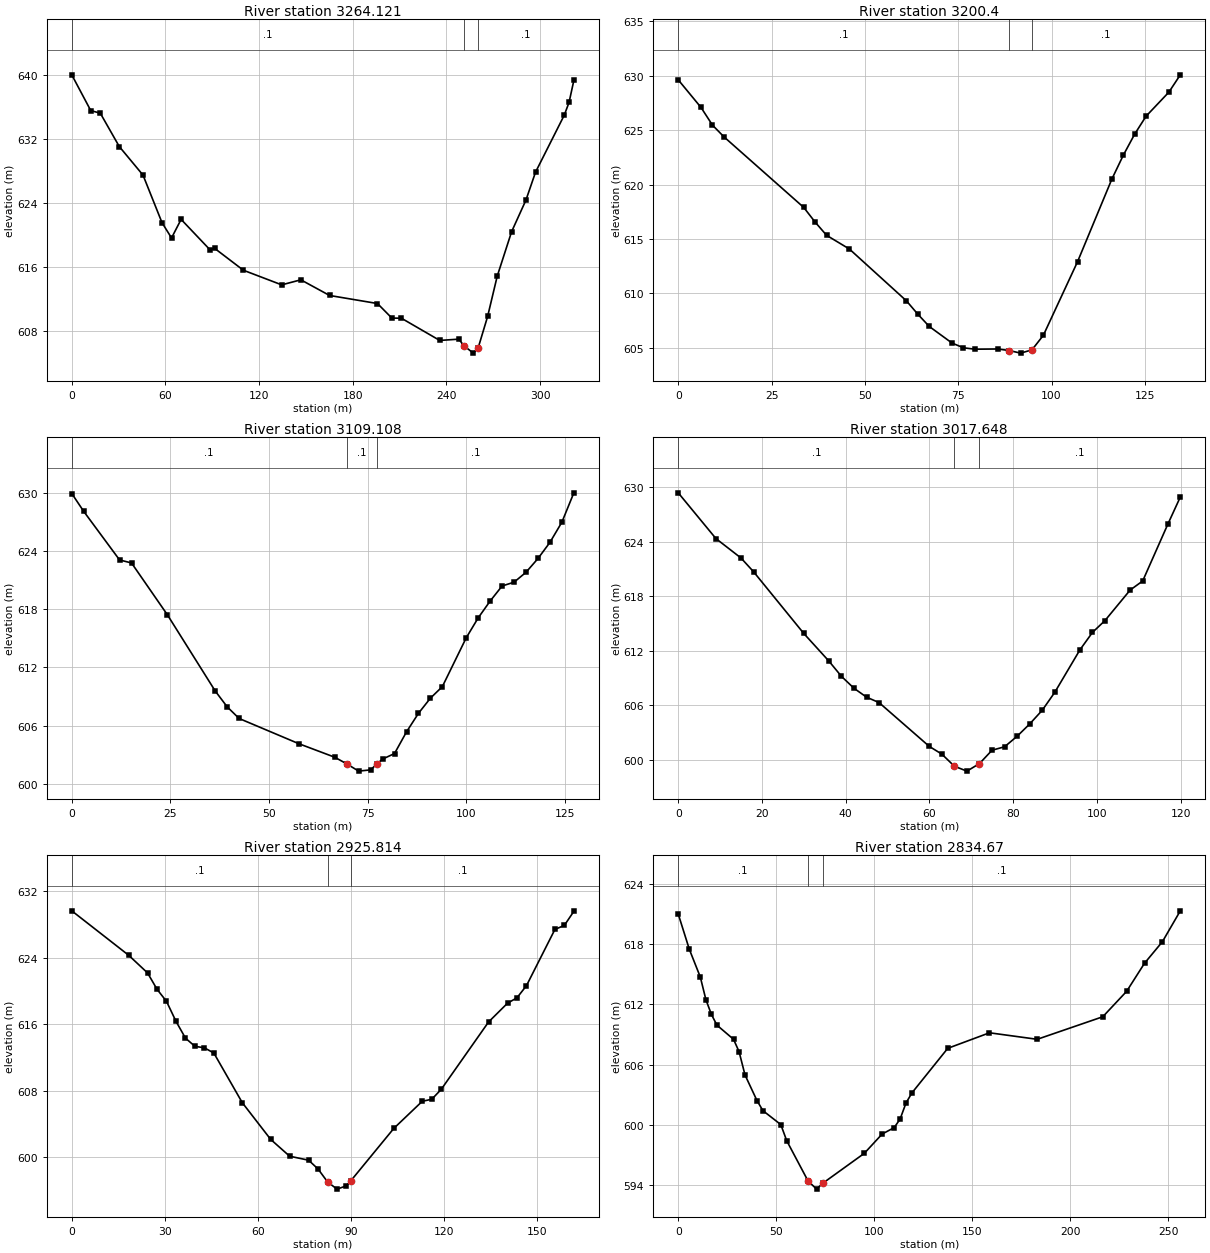
Type RM Length L Ch R = 1 ,3264.121,66.31,63.72,61.13
XS GIS Cut Line= 3
     614941.6402    4324487.0627     614985.5611    4324440.6282
      615206.271    4324307.4924
#Sta/Elev= 30
       0  640.04   12.17  635.56   18.26  635.24   30.44  631.06   45.65  627.48
   57.83  621.52   63.92  619.61   70.05  621.94   88.46  618.15   91.53  618.31
  109.94  615.57  134.49  613.74  146.77  614.37  165.18  612.41  195.86   611.4
  205.07  609.58   211.2  609.56  235.75  606.78  248.03  606.94   251.1  606.14
  257.23  605.19   260.3   605.8  266.44  609.79  272.57  614.82  281.78  620.39
  290.99  624.36  297.12  627.85  315.53  634.99   318.6  636.59  321.67  639.34
#Mann= 3 , 0 , 0
       0      .1       0   251.1      .1       0   260.3      .1       0
Bank Sta=251.1,260.3
XS Rating Curve= 0 ,0
Exp/Cntr=0.3,0.1

Type RM Length L Ch R = 1 ,3200.4  ,102.28,91.29,80.3
XS GIS Cut Line= 2
     615124.9699    4324445.6429     615228.2877    4324359.5447
#Sta/Elev= 26
       0  629.62    6.11  627.08    9.17  625.46   12.23  624.39   33.62   617.9
   36.68  616.55   39.74  615.34   45.85  614.08   61.13  609.32   64.19  608.09
   67.24  606.97   73.36  605.44   76.41  605.01   79.47  604.88   85.58   604.9
   88.64  604.76    91.7  604.52   94.75  604.82   97.81  606.16  106.98  612.93
  116.15   620.5  119.21  622.69  122.26  624.63  125.32  626.28  131.43  628.49
  134.49  630.08
#Mann= 3 , 0 , 0
       0      .1       0   88.64      .1       0   94.75      .1       0
Bank Sta=88.64,94.75
XS Rating Curve= 0 ,0
Exp/Cntr=0.3,0.1

Type RM Length L Ch R = 1 ,3109.108,91.78,91.46,91.14
XS GIS Cut Line= 2
     615249.2242    4324510.9401     615278.8893    4324387.1466
#Sta/Elev= 30
       0   629.9    3.03  628.06   12.12  623.06   15.15  622.75   24.25  617.41
   36.37  609.57    39.4  607.94   42.43  606.74   57.59  604.14   66.68  602.75
   69.71  602.07   72.74  601.32   75.77  601.45   77.47   602.1    78.8  602.56
   81.83  603.13   84.87  605.36    87.9  607.27   90.93  608.83   93.96  610.02
  100.02  615.05  103.05   617.1  106.08  618.83  109.11  620.38  112.14  620.77
  115.17  621.79  118.21  623.21  121.24  624.87  124.27  626.95   127.3  629.97
#Mann= 3 , 0 , 0
       0      .1       0   69.71      .1       0   77.47      .1       0
Bank Sta=69.71,77.47
XS Rating Curve= 0 ,0
Exp/Cntr=0.3,0.1

Type RM Length L Ch R = 1 ,3017.648,84.09,91.83,99.57
XS GIS Cut Line= 2
     615340.7151    4324527.0797     615366.4911    4324409.9278
#Sta/Elev= 28
       0  629.38       9  624.35   14.99  622.21   17.99   620.7   29.99  613.91
   35.99  610.87   38.99  609.19   41.98  607.88   44.98   606.9   47.98   606.3
   59.98  601.48   62.98  600.63   65.97   599.3   68.97  598.76   71.97  599.59
   74.97  601.06   77.97  601.44   80.97   602.6   83.97  603.95   86.97  605.46
   89.97  607.44   95.96   612.1   98.96  614.02  101.96  615.33  107.96  618.68
  110.96  619.68  116.96  625.92  119.95  628.92
#Mann= 3 , 0 , 0
       0      .1       0   65.97      .1       0   71.97      .1       0
Bank Sta=65.97,71.97
XS Rating Curve= 0 ,0
Exp/Cntr=0.3,0.1

Type RM Length L Ch R = 1 ,2925.814,70.33,91.14,111.96
XS GIS Cut Line= 2
     615387.6787    4324560.3732     615488.2206    4324433.3729
#Sta/Elev= 30
       0  629.67   18.34  624.33   24.45   622.2   27.51  620.23   30.56  618.78
   33.62  616.38   36.67  614.36   39.73  613.37   42.79  613.19   45.84  612.56
   55.01  606.59   64.18  602.17   70.29  600.15   76.41  599.67   79.46  598.61
   82.52  597.06   85.57  596.19   88.63  596.59   90.02  597.19  103.91   603.5
  113.08  606.76  116.14     607  119.19  608.19  134.47   616.3  140.59  618.56
  143.64  619.21   146.7  620.67  155.87  627.43  158.92  627.92  161.98  629.61
#Mann= 3 , 0 , 0
       0      .1       0   82.52      .1       0   90.02      .1       0
Bank Sta=82.52,90.02
XS Rating Curve= 0 ,0
Exp/Cntr=0.3,0.1

Type RM Length L Ch R = 1 ,2834.67 ,94.29,91.51,88.73
XS GIS Cut Line= 3
     615410.1495    4324564.0321     615440.7133    4324558.7125
     615656.8046    4324621.5582
#Sta/Elev= 30
       0  621.02    5.64  617.51   11.28  614.72    14.1  612.48   16.92     611
   19.74  609.93    28.2  608.52   31.02  607.29   34.06  604.96   40.15  602.41
   43.19   601.4   52.31  600.01   55.35  598.39   66.19  594.39   70.56  593.57
    73.6  594.14   94.89  597.14  104.01  599.07  110.09   599.7  113.13  600.55
  116.18  602.17  119.22  603.18  137.46  607.62  158.75  609.17  183.08  608.52
  216.53  610.77   228.7  613.31  237.82  616.11  246.94  618.26  256.07  621.34
#Mann= 3 , 0 , 0
       0      .1       0   66.19      .1       0    73.6      .1       0
Bank Sta=66.19,73.6
XS Rating Curve= 0 ,0
Exp/Cntr=0.3,0.1