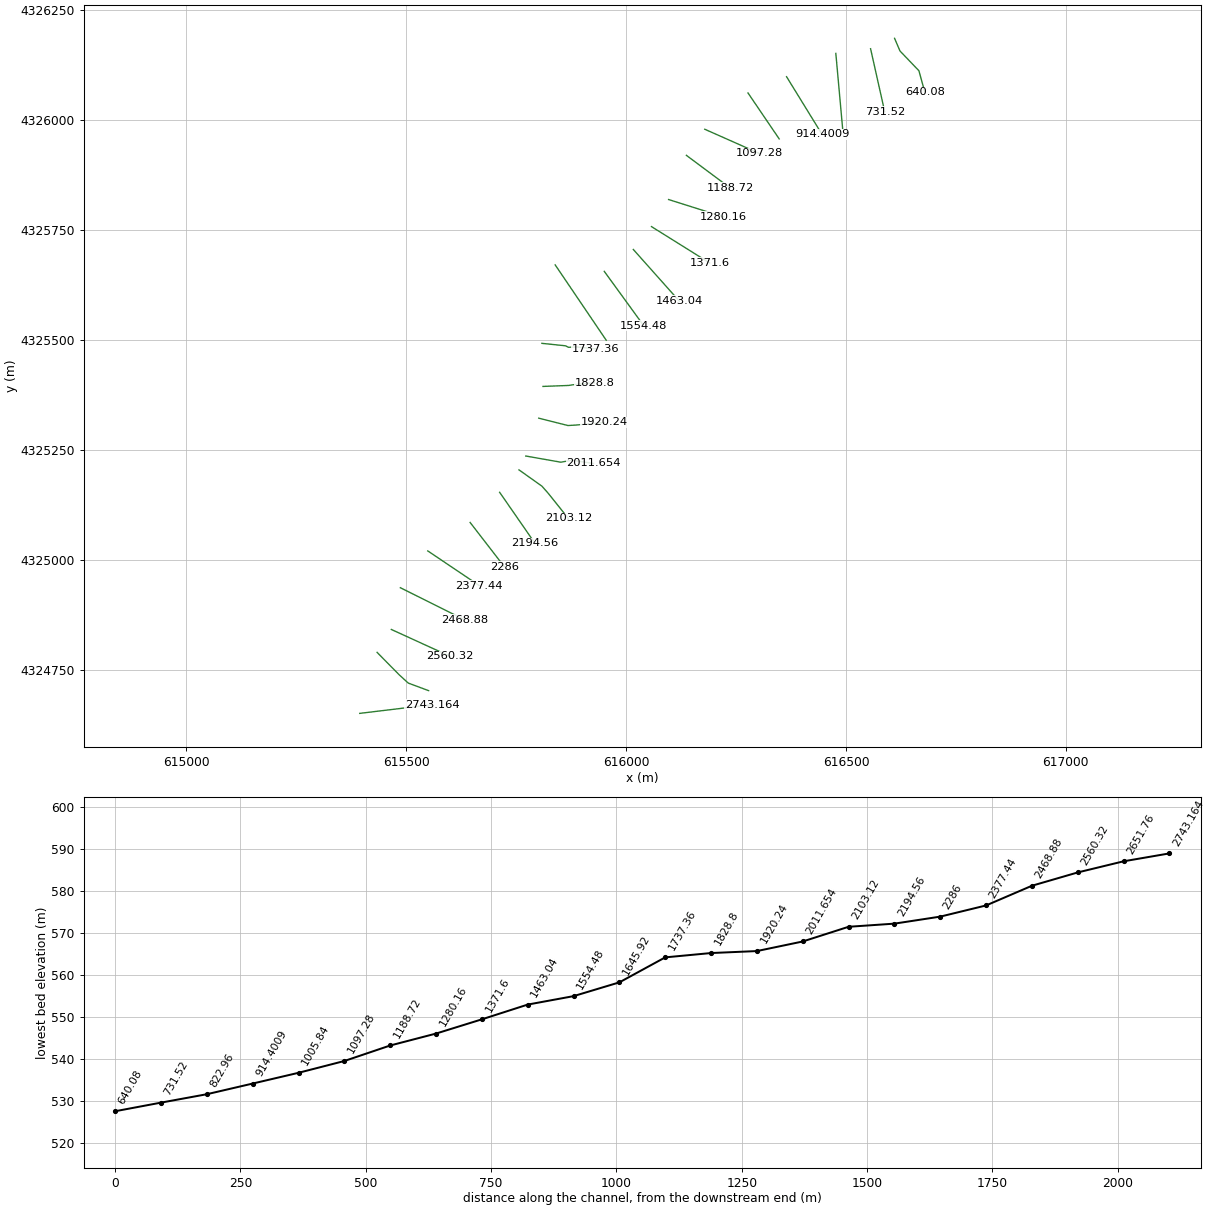
HEC-RAS study ElklickRun.prj: ElklickRun

--- ElklickRun.g01 (geometry) --- (continued)

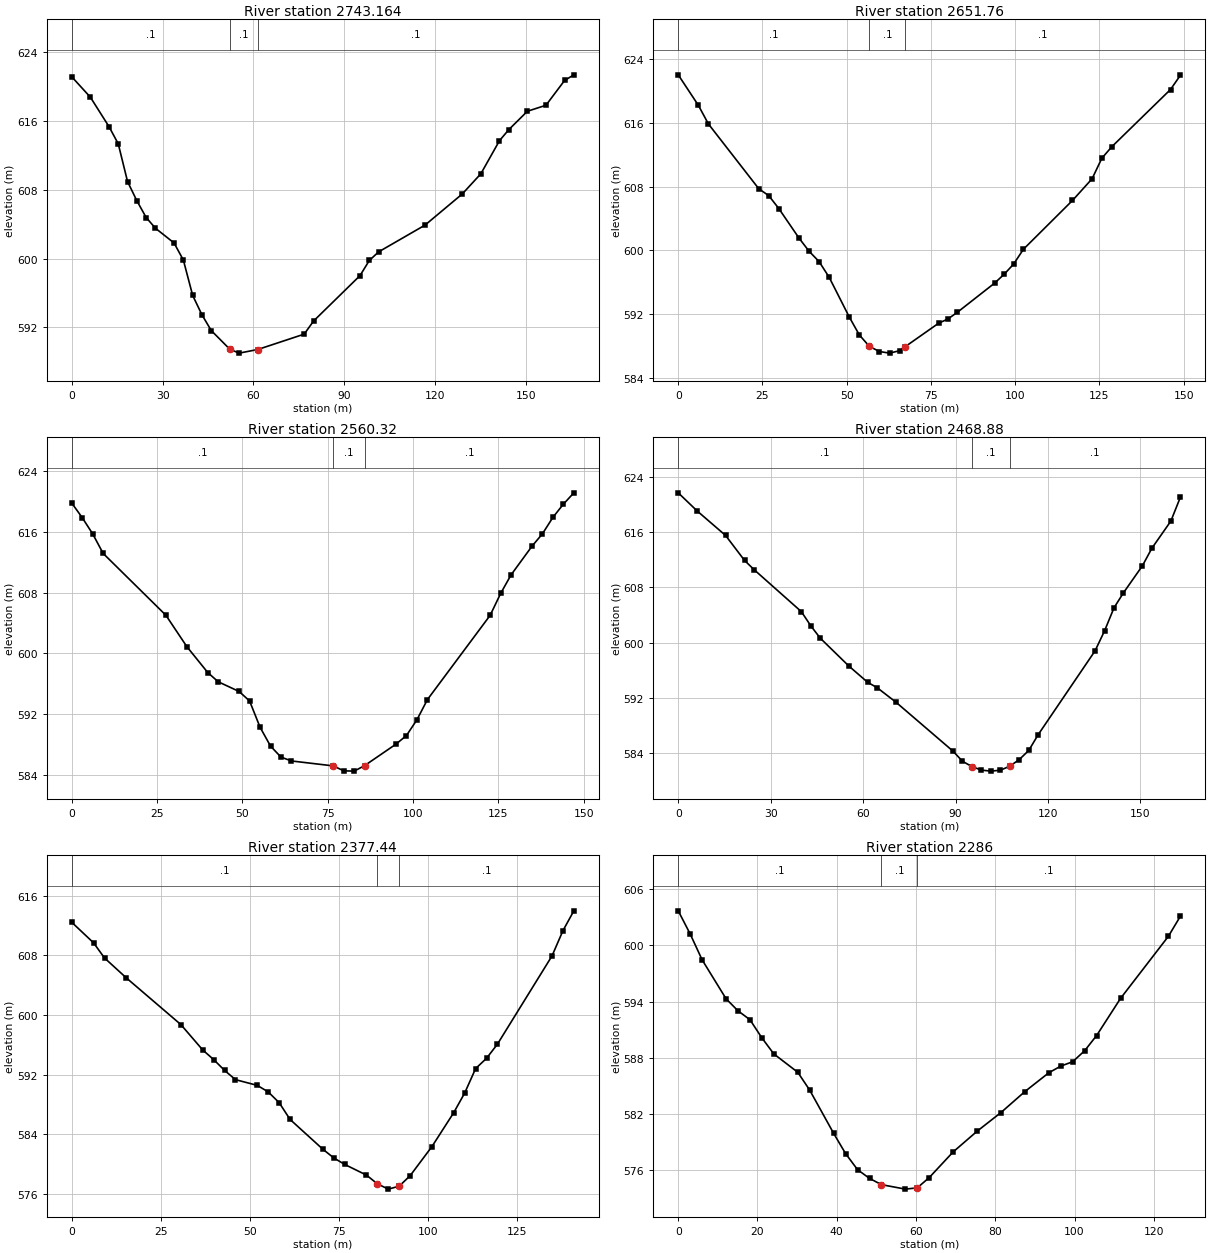
Type RM Length L Ch R = 1 ,2743.164,107.08,91.4,76.33
XS GIS Cut Line= 2
     615394.1125    4324650.8873      615558.816    4324670.7311
#Sta/Elev= 30
       0  621.15    6.14  618.78   12.29  615.36   15.36  613.35   18.43  608.96
    21.5  606.73   24.58  604.78   27.65  603.53   33.79  601.82   36.87  599.83
   39.94  595.72   43.01  593.46   46.08  591.63   52.23  589.45    55.3     589
   61.44  589.42    76.8  591.21   79.88  592.73   95.24  598.02   98.31  599.78
  101.38  600.78  116.74   603.9  129.03  607.52  135.17  609.87  141.32  613.72
  144.39     615  150.53  617.14  156.68  617.84  162.82  620.72  165.89  621.38
#Mann= 3 , 0 , 0
       0      .1       0   52.23      .1       0   61.44      .1       0
Bank Sta=52.23,61.44
XS Rating Curve= 0 ,0
Exp/Cntr=0.3,0.1

Type RM Length L Ch R = 1 ,2651.76 ,85.19,91.44,97.09
XS GIS Cut Line= 4
     615433.5458    4324789.6365     615483.8618    4324738.5881
     615504.4346    4324719.7933     615550.8119     4324702.574
#Sta/Elev= 30
       0     622    5.97  618.18    8.96  615.84   23.89  607.73   26.88  606.85
   29.87  605.23   35.84  601.54   38.83  599.89   41.81  598.59    44.8  596.62
   50.77  591.64   53.76  589.39   56.74  587.96   59.73  587.32   62.72  587.12
    65.7  587.42    67.4  587.94   77.25  590.86   80.04   591.4   82.82  592.23
   93.97  595.92   96.76  597.02   99.54  598.28  102.45  600.14     117  606.25
  122.82  608.97  125.73  611.55  128.64  612.97   146.1  620.16  149.01  621.93
#Mann= 3 , 0 , 0
       0      .1       0   56.74      .1       0    67.4      .1       0
Bank Sta=56.74,67.4
XS Rating Curve= 0 ,0
Exp/Cntr=0.3,0.1

Type RM Length L Ch R = 1 ,2560.32 ,92.02,91.44,90.86
XS GIS Cut Line= 2
     615466.0334    4324841.7021     615599.8151    4324780.5838
#Sta/Elev= 30
       0  619.78    3.06  617.86    6.13  615.72    9.19  613.15   27.58     605
   33.71  600.87   39.83  597.46    42.9  596.24   49.03  594.96   52.09  593.71
   55.16  590.25   58.22  587.77   61.28  586.32   64.35  585.81    76.6  585.16
   79.67  584.51   82.73  584.47    85.8   585.2   94.99  588.03   98.05  589.16
  101.12  591.24  104.18  593.89  122.57     605  125.63  607.87   128.7  610.33
  134.82   614.1  137.89  615.74  140.95   617.9  144.02  619.64  147.08  621.13
#Mann= 3 , 0 , 0
       0      .1       0    76.6      .1       0    85.8      .1       0
Bank Sta=76.6,85.8
XS Rating Curve= 0 ,0
Exp/Cntr=0.3,0.1

Type RM Length L Ch R = 1 ,2468.88 ,93.65,91.44,89.23
XS GIS Cut Line= 2
     615486.5299     4324936.633     615632.3339    4324863.9079
#Sta/Elev= 30
       0  621.76    6.15  619.12   15.37  615.56   21.52  611.93   24.59   610.6
   39.97  604.48   43.04  602.41   46.11  600.62   55.34  596.59   61.48  594.21
   64.56  593.43   70.71   591.3   89.15  584.21   92.23  582.74    95.3  581.96
   98.38  581.45  101.45   581.3  104.52  581.43   107.6  582.02  110.67  582.98
  113.75  584.31  116.82  586.61  135.27  598.79  138.34  601.69  141.42  605.05
  144.49  607.23  150.64  611.16  153.71  613.71  159.86  617.65  162.93   621.1
#Mann= 3 , 0 , 0
       0      .1       0    95.3      .1       0   107.6      .1       0
Bank Sta=95.3,107.6
XS Rating Curve= 0 ,0
Exp/Cntr=0.3,0.1

Type RM Length L Ch R = 1 ,2377.44 ,96.94,91.44,85.94
XS GIS Cut Line= 2
     615548.8827    4325020.3611     615665.9321    4324941.5778
#Sta/Elev= 30
       0  612.44    6.13  609.68     9.2  607.65   15.34  604.97   30.67   598.7
   36.81  595.29   39.87  594.01   42.94  592.55   46.01  591.31   52.14  590.54
   55.21  589.66   58.28  588.22   61.34  585.97   70.55  581.97   73.61  580.81
   76.68  579.93   82.82  578.49   85.88  577.32   88.95  576.61   92.02  577.01
   95.08  578.41  101.22  582.33  107.35  586.89  110.42  589.52  113.49   592.8
  116.56  594.18  119.62  596.08  134.96  607.93  138.03  611.32  141.09  613.98
#Mann= 3 , 0 , 0
       0      .1       0   85.88      .1       0   92.02      .1       0
Bank Sta=85.88,92.02
XS Rating Curve= 0 ,0
Exp/Cntr=0.3,0.1

Type RM Length L Ch R = 1 ,2286    ,92.32,91.44,90.56
XS GIS Cut Line= 2
     615645.1317    4325085.0977     615722.6157    4324984.8503
#Sta/Elev= 30
       0   603.7    3.02  601.22    6.03  598.46   12.07   594.3   15.08  593.01
    18.1  592.06   21.12  590.11   24.13   588.4   30.17  586.44   33.18  584.53
   39.22  579.91   42.23  577.75   45.25  576.03   48.27   575.1   51.28  574.43
   57.32  573.95   60.33  574.09   63.35  575.19   69.38  577.93   75.42  580.14
   81.45  582.14   87.48  584.38   93.52  586.39   96.53   587.1   99.55  587.57
  102.57  588.75  105.58  590.37  111.62  594.34  123.68  600.97   126.7  603.11
#Mann= 3 , 0 , 0
       0      .1       0   51.28      .1       0   60.33      .1       0
Bank Sta=51.28,60.33
XS Rating Curve= 0 ,0
Exp/Cntr=0.3,0.1

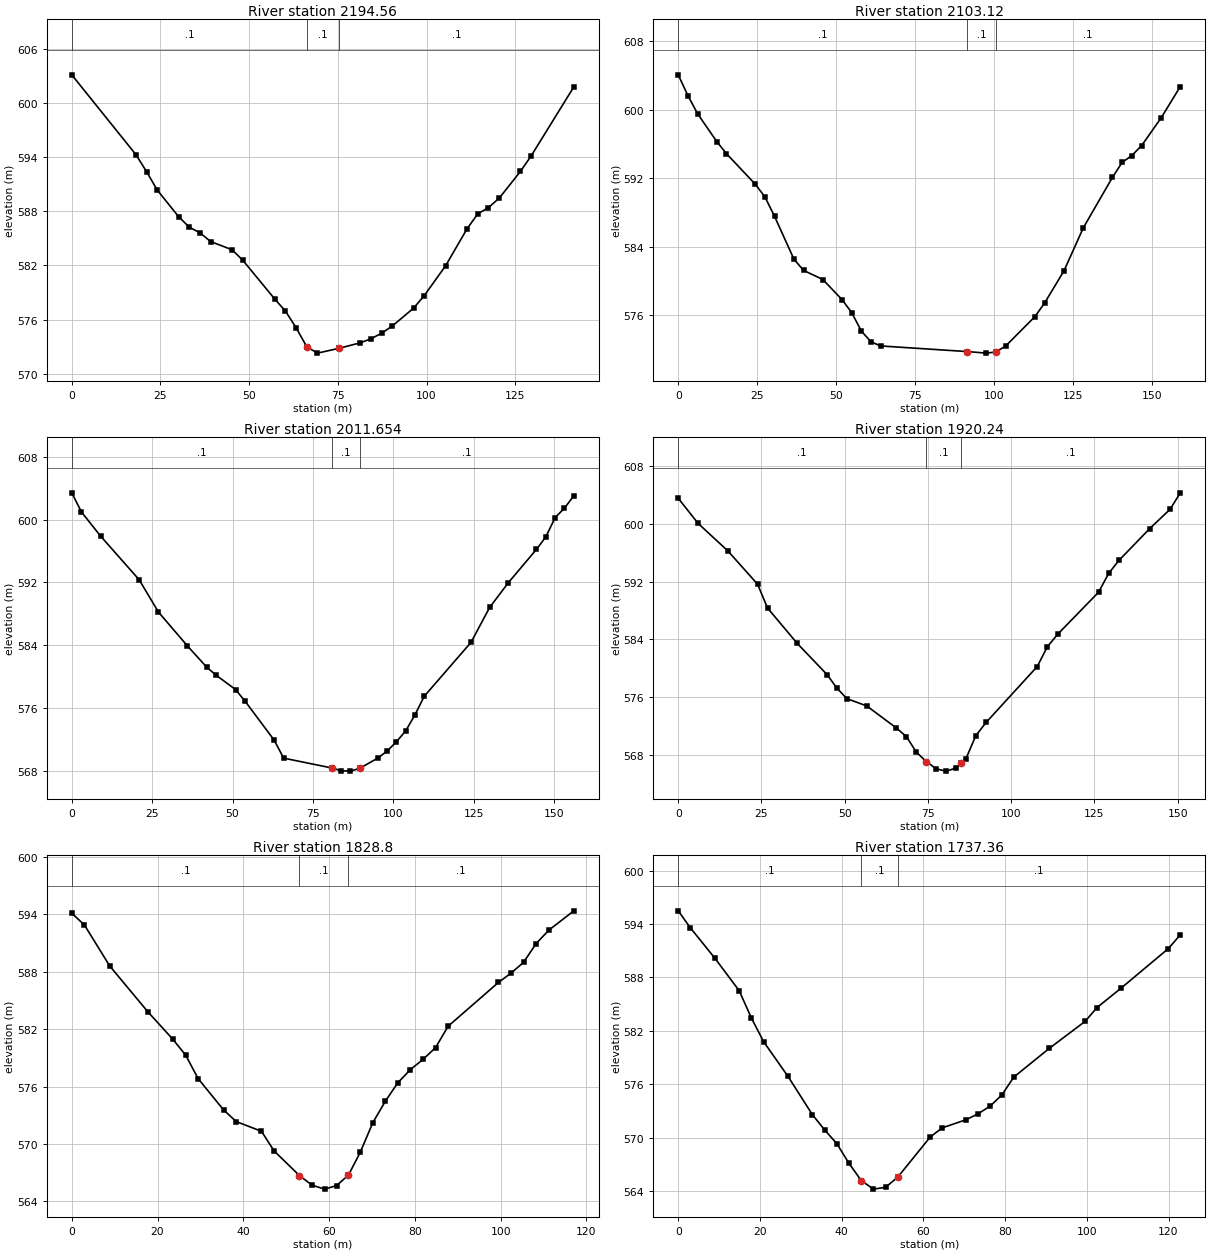
Type RM Length L Ch R = 1 ,2194.56 ,89.25,91.44,92.63
XS GIS Cut Line= 2
      615712.328    4325153.6142     615792.9463    4325037.2927
#Sta/Elev= 30
       0  603.13   18.07  594.29   21.08   592.4   24.09  590.36   30.11  587.41
   33.12  586.24   36.13  585.62   39.15  584.65   45.17  583.74   48.18  582.59
   57.21  578.28   60.22  576.95   63.24  575.09   66.25  572.98   69.26  572.28
   75.28  572.81    81.3  573.42   84.31  573.87   87.33  574.48   90.34  575.28
   96.36  577.27   99.37  578.66  105.39  581.97  111.42  586.06  114.43  587.71
  117.44  588.41  120.45  589.44  126.47  592.42  129.48  594.13  141.53   601.8
#Mann= 3 , 0 , 0
       0      .1       0   66.25      .1       0   75.28      .1       0
Bank Sta=66.25,75.28
XS Rating Curve= 0 ,0
Exp/Cntr=0.3,0.1

Type RM Length L Ch R = 1 ,2103.12 ,79.49,91.47,108.42
XS GIS Cut Line= 4
     615756.2882    4325204.7191     615808.4855    4325167.6279
     615822.4985    4325151.7555      615868.488    4325094.2688
#Sta/Elev= 30
       0  604.08    3.05  601.66     6.1  599.54    12.2  596.27   15.25  594.86
   24.39  591.28   27.44  589.79   30.49  587.51   36.59  582.53   39.64  581.21
   45.74  580.14   51.84  577.78   54.89  576.26   57.94   574.1   60.98  572.86
   64.03  572.37   91.49  571.71   97.48  571.53  100.54  571.67  103.61  572.37
  112.81  575.79  115.88  577.38  122.02  581.15  128.15  586.19  137.35  592.08
  140.42  593.83  143.49  594.64  146.56  595.79  152.69     599  158.83  602.71
#Mann= 3 , 0 , 0
       0      .1       0   91.49      .1       0  100.54      .1       0
Bank Sta=91.49,100.54
XS Rating Curve= 0 ,0
Exp/Cntr=0.3,0.1

Type RM Length L Ch R = 1 ,2011.654,88.09,91.41,98.06
XS GIS Cut Line= 4
     615771.7266    4325236.2174     615851.3894    4325222.1784
     615876.8275    4325226.6434     615925.7144     4325219.284
#Sta/Elev= 30
       0  603.39       3  600.96    8.99  597.88   20.97  592.34   26.96  588.24
   35.95  583.95   41.94  581.25   44.94   580.2   50.93   578.4   53.93   576.9
   62.91  571.99   65.91  569.68   80.89  568.43   83.76  568.08   86.63  568.03
    89.5  568.37   95.24   569.7   98.11  570.59  100.98  571.76  103.85  573.14
  106.72  575.16  109.63  577.54  124.17  584.39  129.98  588.83   135.8  591.98
  144.52   596.2  147.43  597.79  150.34  600.24  153.25  601.45  156.16  603.02
#Mann= 3 , 0 , 0
       0      .1       0   80.89      .1       0    89.5      .1       0
Bank Sta=80.89,89.5
XS Rating Curve= 0 ,0
Exp/Cntr=0.3,0.1

Type RM Length L Ch R = 1 ,1920.24 ,87.58,91.44,92.4
XS GIS Cut Line= 4
     615801.1949    4325322.2837     615867.6653    4325305.5519
     615888.4857    4325306.8028     615949.6453    4325312.4627
#Sta/Elev= 30
       0  603.54    5.96  600.06    14.9  596.25   23.84  591.63   26.82  588.34
   35.76  583.43    44.7  579.12   47.68  577.23   50.66  575.79   56.62  574.78
   65.56  571.71   68.54  570.53   71.52  568.38    74.5  567.08   77.48  566.07
   80.46  565.75   83.44  566.17   85.03  566.89   86.42  567.46    89.4  570.67
   92.47  572.49  107.83  580.23   110.9  582.98  113.97   584.7  126.25  590.52
  129.33  593.15   132.4  594.94  141.61  599.33  147.75  602.01  150.82  604.29
#Mann= 3 , 0 , 0
       0      .1       0    74.5      .1       0   85.03      .1       0
Bank Sta=74.5,85.03
XS Rating Curve= 0 ,0
Exp/Cntr=0.3,0.1

Type RM Length L Ch R = 1 ,1828.8  ,93.53,91.44,85.36
XS GIS Cut Line= 4
     615810.8468    4325394.4854     615869.7712    4325396.7405
     615877.9227    4325398.1436      615927.507    4325402.8449
#Sta/Elev= 30
       0   594.1    2.95  592.87    8.85  588.59   17.69  583.83   23.59  580.92
   26.54  579.28   29.48  576.81   35.38  573.56   38.33  572.34   44.23  571.32
   47.17  569.27   53.07   566.7   56.02  565.69   58.97  565.28   61.72  565.65
   64.48  566.73   67.24  569.11   70.17  572.21    73.1  574.46   76.03   576.4
   78.96  577.77   81.89  578.83   84.82  580.07   87.75   582.3   99.47  586.87
   102.4  587.84  105.33  588.97  108.26  590.93  111.19  592.32  117.05  594.35
#Mann= 3 , 0 , 0
       0      .1       0   53.07      .1       0   64.48      .1       0
Bank Sta=53.07,64.48
XS Rating Curve= 0 ,0
Exp/Cntr=0.3,0.1

Type RM Length L Ch R = 1 ,1737.36 ,105.35,91.44,75.9
XS GIS Cut Line= 5
     615808.3968    4325492.4644     615861.8704    4325486.9326
     615868.9826    4325483.4529     615886.5005    4325484.3846
     615929.9478    4325480.0049
#Sta/Elev= 28
       0  595.48    2.99  593.56    8.96  590.17   14.93  586.51   17.92  583.44
   20.91  580.79   26.88  576.89   32.85   572.6   35.84  570.89   38.83  569.35
   41.81  567.13    44.8  565.21   47.79  564.25   50.77  564.46   53.76  565.61
   61.68   570.1    64.6  571.12   70.45  572.04   73.37   572.7    76.3  573.55
   79.22  574.82   82.13  576.82   90.86  580.06    99.6  583.08  102.51  584.63
  108.33  586.78  119.98  591.25  122.89  592.79
#Mann= 3 , 0 , 0
       0      .1       0    44.8      .1       0   53.76      .1       0
Bank Sta=44.8,53.76
XS Rating Curve= 0 ,0
Exp/Cntr=0.3,0.1

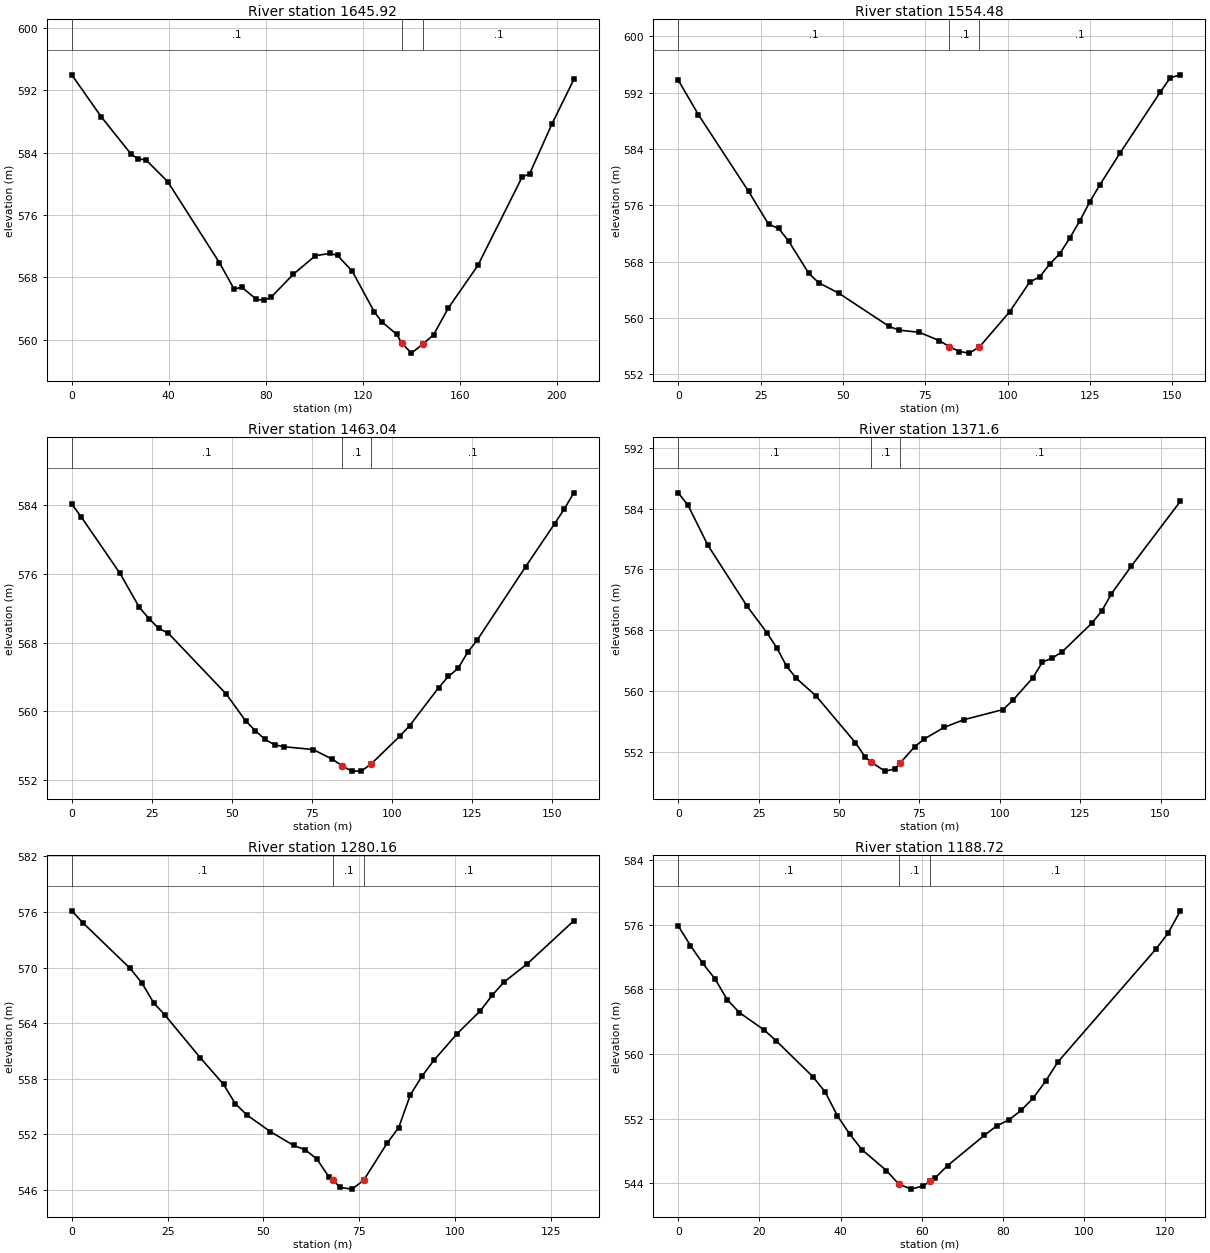
Type RM Length L Ch R = 1 ,1645.92 ,90.97,91.44,91.91
XS GIS Cut Line= 2
     615838.5705    4325670.9525     615954.6667    4325499.5723
#Sta/Elev= 30
       0  593.95   12.18  588.56   24.35  583.83    27.4  583.14   30.44   583.1
   39.57  580.26   60.88  569.88   66.97  566.48   70.02  566.76    76.1   565.2
   79.15  565.06   82.19  565.46   91.32   568.4  100.46  570.78  106.54  571.08
  109.59  570.81  115.68  568.77  124.81  563.54  127.85  562.31  133.94  560.71
  136.09  559.57  140.03   558.3  144.76  559.46  149.16  560.65  155.25  564.08
  167.43  569.53  185.69  580.87  188.74  581.25  197.87  587.59     207  593.36
#Mann= 3 , 0 , 0
       0      .1       0  136.09      .1       0  144.76      .1       0
Bank Sta=136.09,144.76
XS Rating Curve= 0 ,0
Exp/Cntr=0.3,0.1

Type RM Length L Ch R = 1 ,1554.48 ,89.75,91.44,93.13
XS GIS Cut Line= 2
     615950.1802    4325656.2828     616039.7591    4325532.9505
#Sta/Elev= 30
       0  593.77     6.1  588.88   21.34  577.99   27.44   573.3   30.49  572.72
   33.53  570.91   39.63  566.34   42.68     565   48.78  563.52   64.02  558.81
   67.07  558.28   73.17  557.98   79.26   556.8   82.31  555.93   85.36  555.25
   88.41  555.02   91.46  555.91   100.6  560.88   106.7   565.1  109.75  565.85
   112.8  567.66  115.85  569.14   118.9  571.37  121.94  573.82  124.99  576.52
  128.04  578.93  134.14  583.43  146.33  592.06  149.38   594.1  152.43  594.52
#Mann= 3 , 0 , 0
       0      .1       0   82.31      .1       0   91.46      .1       0
Bank Sta=82.31,91.46
XS Rating Curve= 0 ,0
Exp/Cntr=0.3,0.1

Type RM Length L Ch R = 1 ,1463.04 ,86.45,91.44,96.43
XS GIS Cut Line= 2
     616016.3103    4325705.9749     616120.7174    4325588.7923
#Sta/Elev= 30
       0  584.15    3.02  582.62   15.09  576.06   21.13   572.1   24.15  570.79
   27.16  569.66   30.18  569.09   48.29     562   54.33  558.88   57.35  557.74
   60.36  556.73   63.38  556.08    66.4  555.85   75.46  555.53   81.49  554.39
   84.51  553.62   87.53  553.01   90.55  553.02   93.57  553.84  102.62  557.11
  105.64  558.32  114.69  562.74  117.71  564.05  120.73  564.98  123.75  566.86
  126.77  568.31  141.86  576.84  150.91  581.84  153.93  583.56  156.95  585.46
#Mann= 3 , 0 , 0
       0      .1       0   84.51      .1       0   93.57      .1       0
Bank Sta=84.51,93.57
XS Rating Curve= 0 ,0
Exp/Cntr=0.3,0.1

Type RM Length L Ch R = 1 ,1371.6  ,87.13,91.44,95.78
XS GIS Cut Line= 2
     616057.5686    4325758.0313     616189.9914    4325675.2671
#Sta/Elev= 30
       0  586.06    3.06  584.41    9.19  579.19   21.43  571.16   27.56  567.69
   30.62  565.72   33.68  563.29   36.74  561.69   42.87  559.38   55.12  553.23
   58.18  551.33   60.05  550.66    64.3   549.5   67.36  549.79   68.97  550.54
   73.49  552.69   76.55  553.73   82.67  555.24    88.8  556.25  101.04  557.59
  104.11  558.82  110.23  561.73  113.29  563.83  116.35  564.36  119.42  565.18
   128.6  568.92  131.66  570.49  134.73  572.79  140.85  576.39  156.16  584.94
#Mann= 3 , 0 , 0
       0      .1       0   60.05      .1       0   68.97      .1       0
Bank Sta=60.05,68.97
XS Rating Curve= 0 ,0
Exp/Cntr=0.3,0.1

Type RM Length L Ch R = 1 ,1280.16 ,97.15,91.44,85.7
XS GIS Cut Line= 2
      616096.547     4325819.547     616221.4898    4325780.0912
#Sta/Elev= 30
       0  576.11    3.05  574.76   15.24   569.9   18.28  568.35   21.33  566.22
   24.38  564.84   33.52  560.28   39.61   557.4   42.66  555.33   45.71   554.1
    51.8  552.32   57.89  550.82   60.94  550.35   63.99  549.34   67.04  547.47
   68.13  547.08   70.08  546.29   73.13  546.11   76.18  547.07   82.27  551.05
   85.32  552.75   88.37  556.29   91.41  558.29   94.46  559.98  100.55  562.86
  106.65  565.35   109.7     567  112.74  568.41  118.84  570.39  131.02  575.04
#Mann= 3 , 0 , 0
       0      .1       0   68.13      .1       0   76.18      .1       0
Bank Sta=68.13,76.18
XS Rating Curve= 0 ,0
Exp/Cntr=0.3,0.1

Type RM Length L Ch R = 1 ,1188.72 ,87.28,91.44,95.6
XS GIS Cut Line= 2
     616137.0233    4325920.0465     616236.2277    4325846.1703
#Sta/Elev= 30
       0  575.87    3.02  573.42    6.03  571.23    9.05  569.31   12.07  566.73
   15.08  565.12   21.12     563   24.13  561.64   33.19  557.18    36.2   555.3
   39.22  552.34   42.24  550.09   45.25  548.16   51.29  545.57    54.3  543.91
   57.32  543.27   60.34  543.66   62.11  544.27   63.35  544.69   66.37  546.19
   75.42  549.93   78.44   551.1   81.45  551.84   84.47  553.02   87.49  554.58
    90.5  556.63   93.52  559.01  117.66  572.98  120.67  574.95  123.69  577.73
#Mann= 3 , 0 , 0
       0      .1       0    54.3      .1       0   62.11      .1       0
Bank Sta=54.3,62.11
XS Rating Curve= 0 ,0
Exp/Cntr=0.3,0.1

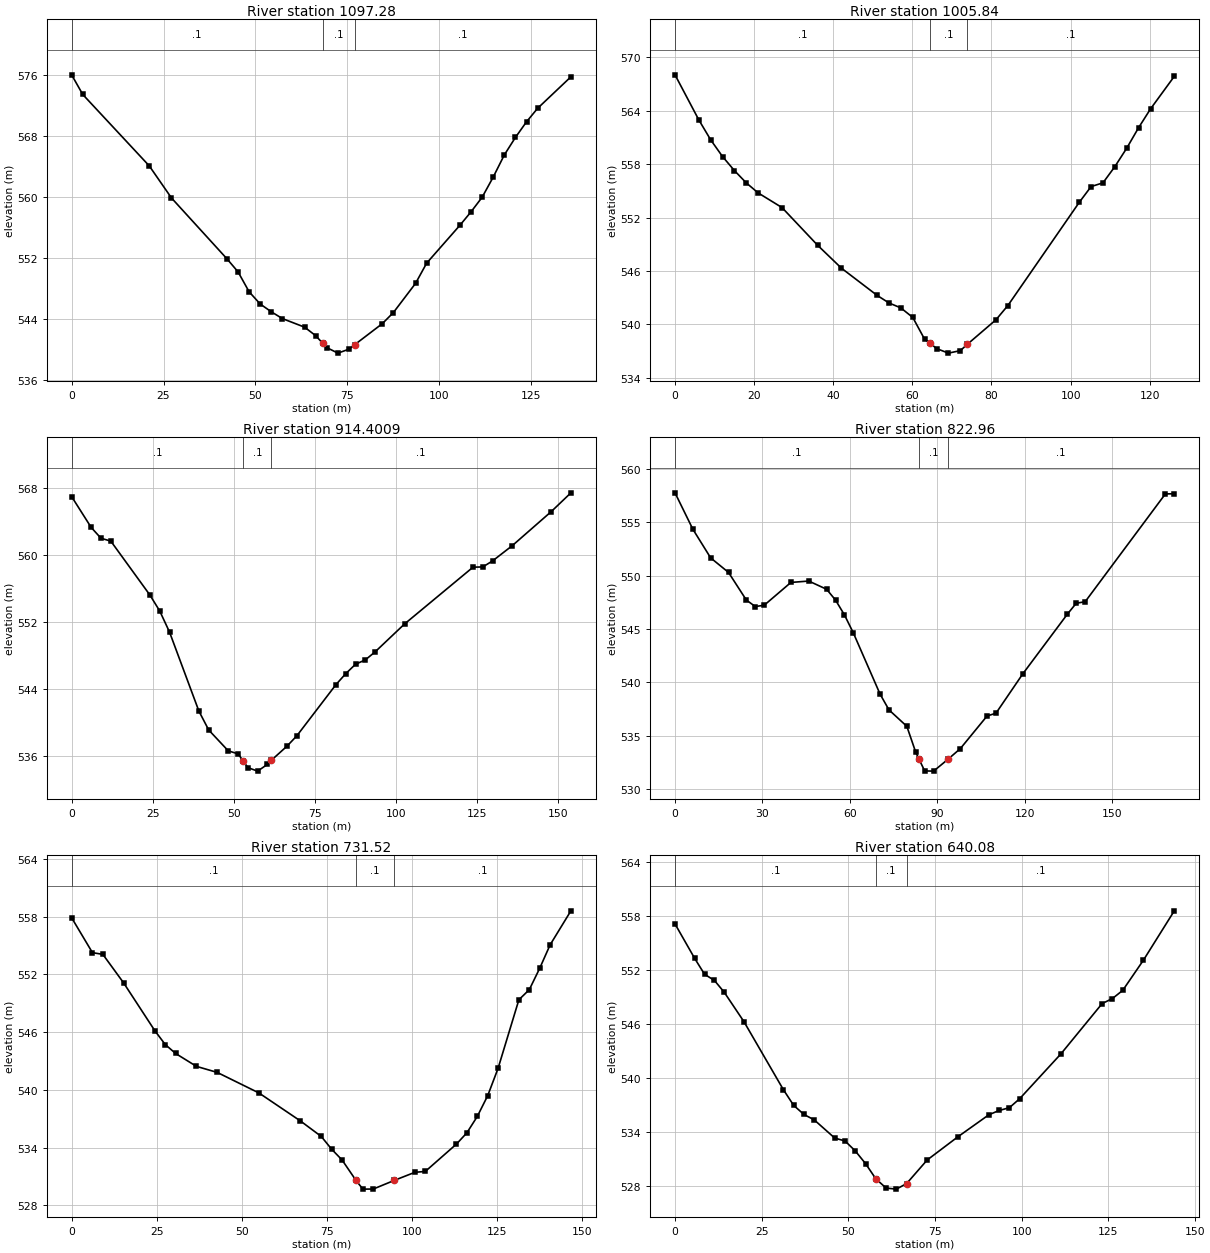
Type RM Length L Ch R = 1 ,1097.28 ,101.12,91.44,81.76
XS GIS Cut Line= 2
     616178.7893    4325979.4338     616302.9212    4325924.3674
#Sta/Elev= 30
       0  576.03    3.02  573.46   21.12   564.1   27.16   559.9   42.25  551.93
   45.27  550.22   48.28  547.61    51.3  546.01   54.32  544.99   57.34   544.1
   63.37  542.98   66.39  541.86   68.32  540.86   69.41   540.3   72.43  539.58
   75.44   540.1   77.01  540.69    84.5  543.44   87.51  544.89   93.55  548.72
   96.57  551.37  105.62  556.33  108.64  558.09  111.66     560  114.67  562.64
  117.69  565.54  120.71  567.83  123.73  569.88  126.74  571.64   135.8  575.77
#Mann= 3 , 0 , 0
       0      .1       0   68.32      .1       0   77.01      .1       0
Bank Sta=68.32,77.01
XS Rating Curve= 0 ,0
Exp/Cntr=0.3,0.1

Type RM Length L Ch R = 1 ,1005.84 ,92.17,91.44,90.71
XS GIS Cut Line= 2
      616277.159    4326061.8842     616348.0684    4325957.4641
#Sta/Elev= 30
       0  568.05    6.01  562.99    9.02  560.74   12.02  558.86   15.03  557.28
   18.03   555.9   21.04  554.77   27.05  553.13   36.06  548.89   42.07  546.32
   51.09  543.26   54.09  542.41    57.1  541.85   60.11  540.78   63.11  538.32
   64.57  537.86   66.12  537.28   69.12  536.77   72.13  537.05   73.87  537.75
   81.14  540.52   84.15  542.12  102.18  553.71  105.18  555.49  108.19  555.91
  111.19  557.73   114.2  559.81  117.21  562.12  120.21  564.22  126.22  567.88
#Mann= 3 , 0 , 0
       0      .1       0   64.57      .1       0   73.87      .1       0
Bank Sta=64.57,73.87
XS Rating Curve= 0 ,0
Exp/Cntr=0.3,0.1

Type RM Length L Ch R = 1 ,914.4009,99.37,91.44,83.51
XS GIS Cut Line= 2
     616364.8066    4326098.9389     616445.4696    4325967.9483
#Sta/Elev= 30
       0  566.96    6.03  563.28    9.05  561.99   12.07  561.65   24.13  555.21
   27.15  553.31   30.16   550.8   39.21  541.37   42.23  539.12   48.26  536.63
   51.28  536.27   52.95  535.38   54.29  534.63   57.31  534.21   60.33  535.02
   61.52   535.5   66.36  537.19   69.38  538.42   81.44  544.53   84.46  545.84
   87.47  546.96   90.49  547.48   93.51  548.44  102.56  551.76  123.67  558.54
  126.69  558.57   129.7  559.29  135.74   561.1   147.8  565.18  153.83  567.41
#Mann= 3 , 0 , 0
       0      .1       0   52.95      .1       0   61.52      .1       0
Bank Sta=52.95,61.52
XS Rating Curve= 0 ,0
Exp/Cntr=0.3,0.1

Type RM Length L Ch R = 1 ,822.96  ,89.22,91.44,93.66
XS GIS Cut Line= 2
     616476.9198    4326151.9012     616492.3301    4325981.2026
#Sta/Elev= 30
       0  557.76    6.12  554.35   12.24  551.66   18.36   550.3   24.48  547.71
   27.55   547.1   30.61  547.22   39.79  549.36   45.91  549.49   52.03  548.72
   55.09  547.71   58.15  546.32   61.21  544.63   70.39  538.89   73.45  537.41
   79.58  535.87   82.64  533.43   83.76  532.79    85.7  531.69   88.76  531.67
   93.74  532.79   97.94  533.78  107.12  536.84  110.18   537.1  119.36  540.78
  134.67  546.38  137.73  547.41  140.79  547.55  168.33  557.66  171.39  557.67
#Mann= 3 , 0 , 0
       0      .1       0   83.76      .1       0   93.74      .1       0
Bank Sta=83.76,93.74
XS Rating Curve= 0 ,0
Exp/Cntr=0.3,0.1

Type RM Length L Ch R = 1 ,731.52  ,82,91.44,100.88
XS GIS Cut Line= 2
     616555.9182    4326162.5814     616588.0141     4326019.487
#Sta/Elev= 30
       0   557.9    6.11  554.27    9.17  554.09   15.28  551.12   24.44  546.15
    27.5  544.71   30.55  543.78   36.66  542.44   42.77  541.81   54.99  539.68
   67.21  536.76   73.32  535.15   76.38  533.82   79.44   532.7   83.54  530.57
   85.55  529.67    88.6  529.68   94.71  530.57  100.82  531.42  103.88  531.51
  113.04  534.36   116.1  535.53  119.15  537.23  122.21  539.39  125.26  542.24
  131.37  549.37  134.43  550.42  137.48  552.64  140.54  555.08  146.65  558.62
#Mann= 3 , 0 , 0
       0      .1       0   83.54      .1       0   94.71      .1       0
Bank Sta=83.54,94.71
XS Rating Curve= 0 ,0
Exp/Cntr=0.3,0.1

Type RM Length L Ch R = 1 ,640.08  ,179.44,182.88,186.32
XS GIS Cut Line= 4
     616610.5037    4326186.1748     616622.7928    4326157.4372
     616665.8173    4326112.5143     616679.2956    4326063.8048
#Sta/Elev= 30
       0  557.13    5.68  553.29    8.52  551.53   11.37  550.84   14.21  549.52
   19.89  546.25   31.25  538.69   34.22  536.94   37.18  535.93   40.14  535.33
   46.07   533.3   49.03  532.98   51.99  531.87   54.95  530.46   57.91  528.77
   60.88  527.74   63.84  527.62    66.8  528.24   72.72  530.86   81.61  533.45
    90.5  535.89   93.46  536.37   96.43  536.68    99.4  537.68   111.3  542.67
  123.19  548.27  126.16  548.83  129.13  549.74  135.08  553.09     144  558.59
#Mann= 3 , 0 , 0
       0      .1       0   57.91      .1       0    66.8      .1       0
Bank Sta=57.91,66.8
XS Rating Curve= 0 ,0
Exp/Cntr=0.3,0.1