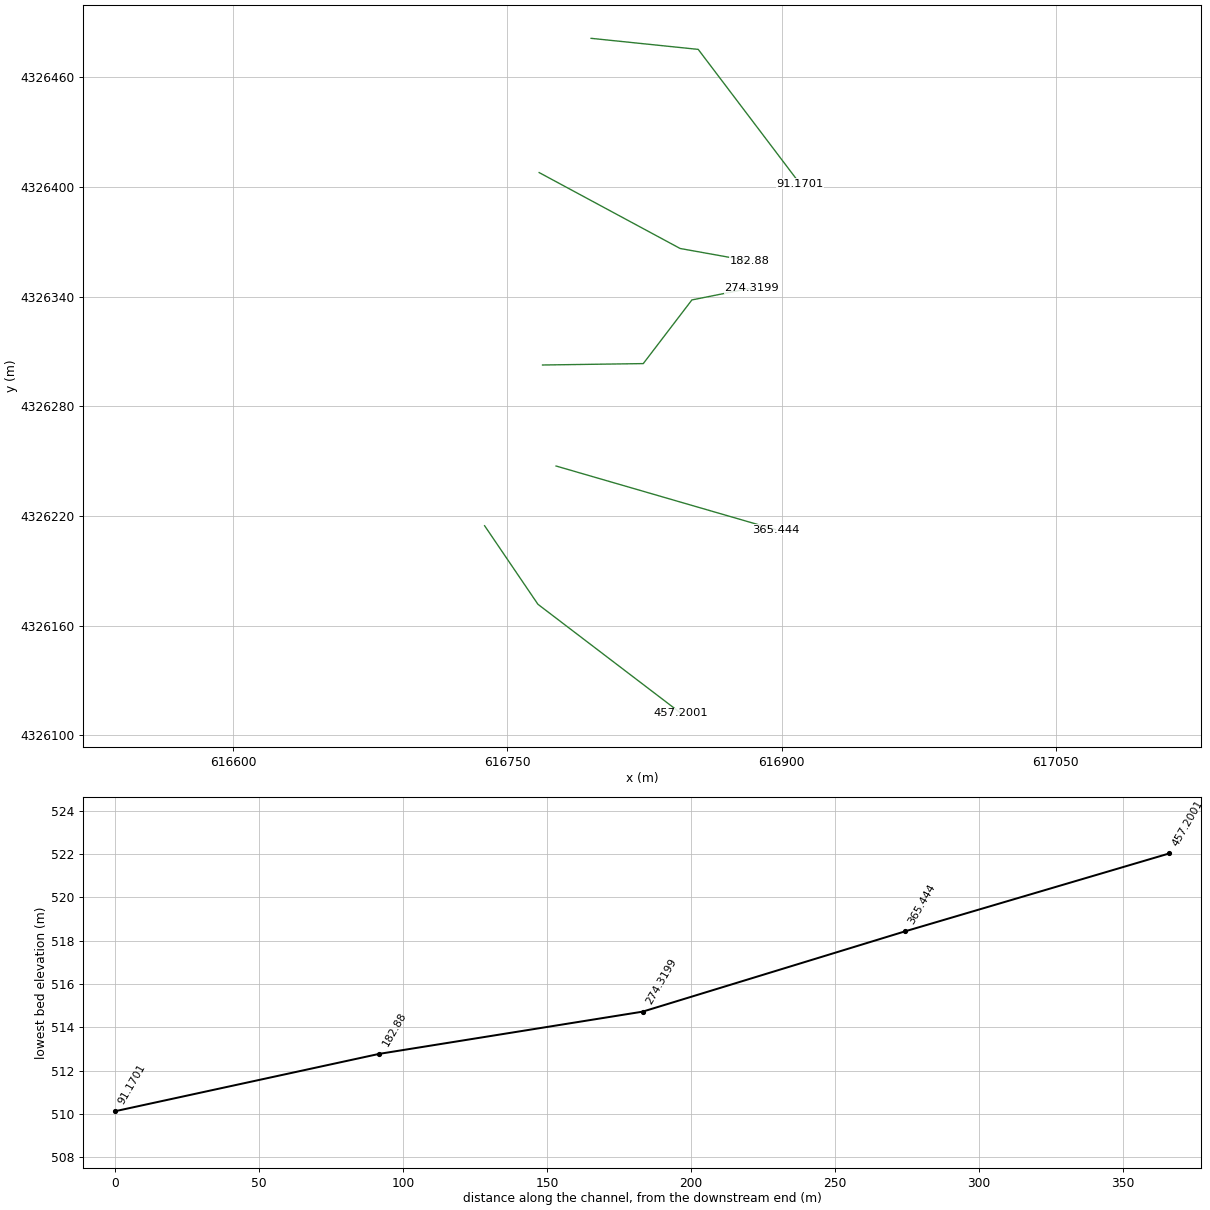
HEC-RAS study ElklickRun.prj: ElklickRun

--- ElklickRun.g01 (geometry) --- (continued)

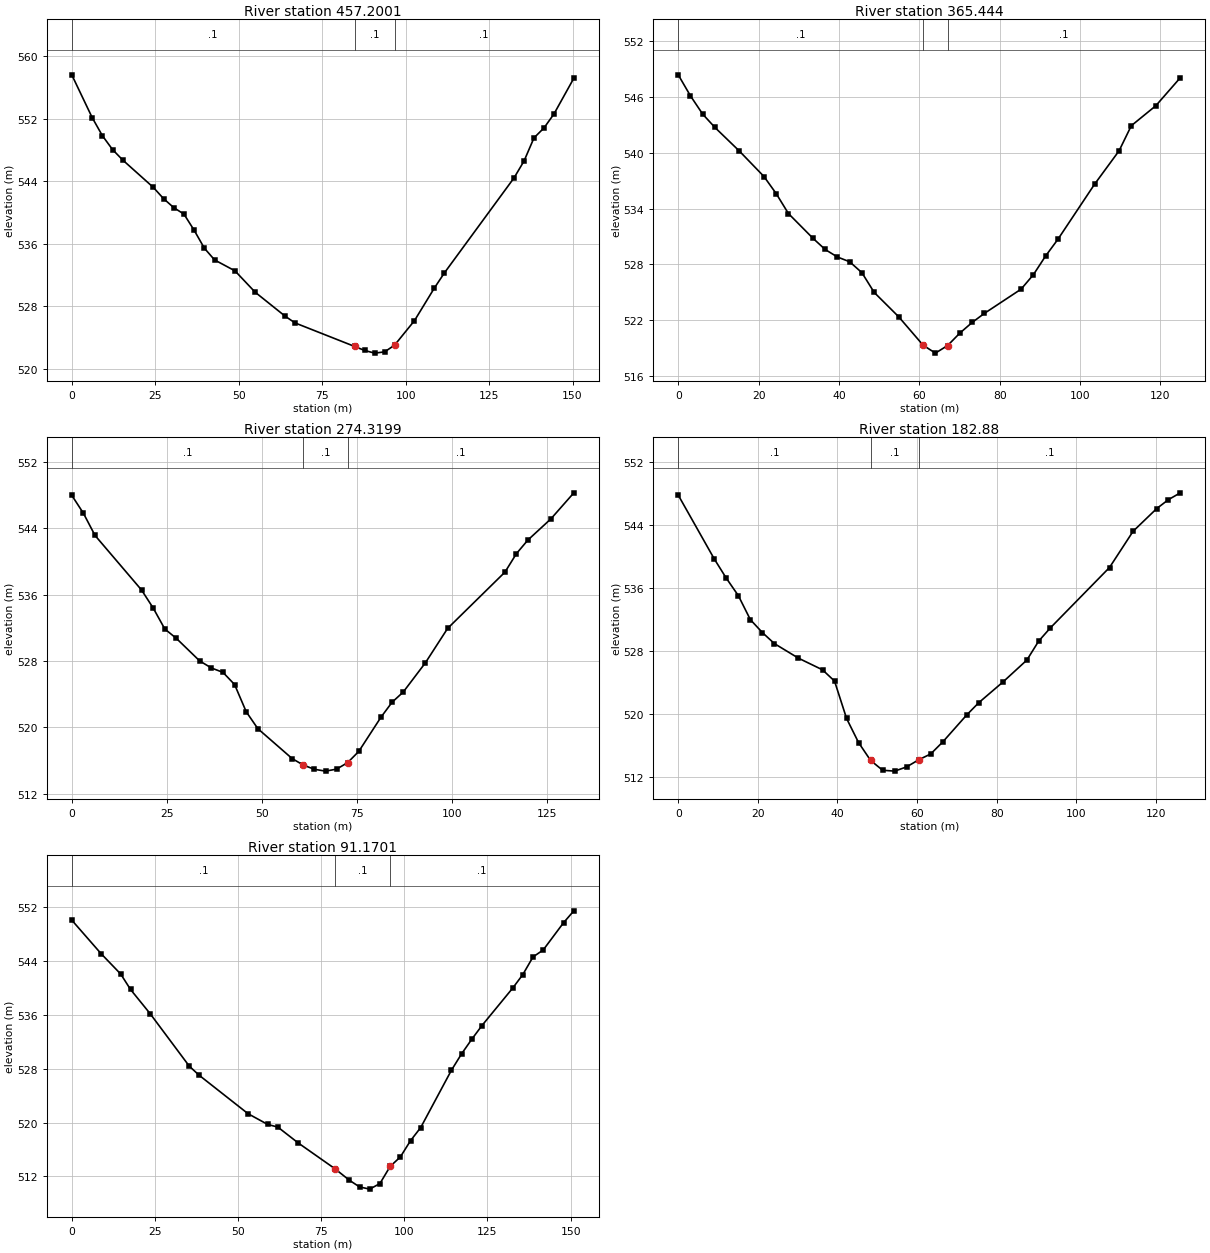
Type RM Length L Ch R = 1 ,457.2001,85.38,91.76,98.13
XS GIS Cut Line= 3
      616737.504    4326214.6176     616766.6856    4326171.6458
     616844.9994    4326111.9781
#Sta/Elev= 30
       0  557.65    6.11  552.18    9.17  549.86   12.22  548.08   15.28  546.74
   24.44  543.24    27.5   541.8   30.56  540.65   33.61  539.82   36.67  537.75
   39.72  535.46   42.78  533.96   48.89  532.56   54.93  529.83   63.88  526.77
   66.86   525.9   84.76  522.88   87.75  522.37   90.73  522.03   93.71  522.19
    96.7  523.05  102.66  526.19  108.63  530.37  111.61  532.29   132.5  544.47
  135.48  546.62  138.46  549.58  141.45  550.85  144.43  552.63   150.4  557.22
#Mann= 3 , 0 , 0
       0      .1       0   84.76      .1       0    96.7      .1       0
Bank Sta=84.76,96.7
XS Rating Curve= 0 ,0
Exp/Cntr=0.3,0.1

Type RM Length L Ch R = 1 ,365.444 ,77.49,91.12,112.42
XS GIS Cut Line= 2
     616776.5963    4326247.2937     616896.6192    4326212.4914
#Sta/Elev= 30
       0   548.4    3.05  546.13     6.1  544.16    9.14  542.73   15.24  540.18
   21.34  537.45   24.38  535.61   27.43  533.46   33.53   530.8   36.58  529.59
   39.62  528.78   42.67  528.27   45.72  527.09   48.77  524.97   54.86  522.35
   60.96  519.28   64.01  518.43   67.06  519.25    70.1  520.59   73.15  521.73
    76.2  522.71   85.34  525.32   88.39  526.87   91.44  528.89   94.49  530.68
  103.63  536.62  109.73  540.22  112.77  542.92  118.87  545.07  124.97  548.09
#Mann= 3 , 0 , 0
       0      .1       0   60.96      .1       0   67.06      .1       0
Bank Sta=60.96,67.06
XS Rating Curve= 0 ,0
Exp/Cntr=0.3,0.1

Type RM Length L Ch R = 1 ,274.3199,112.24,91.44,62.98
XS GIS Cut Line= 4
     616769.1996    4326302.5499     616824.2968    4326303.3187
     616850.8989    4326338.1431     616883.4881    4326344.6606
#Sta/Elev= 30
       0  547.98    3.06  545.82    6.12  543.14   18.37  536.56   21.43  534.39
   24.49  531.86   27.55  530.72   33.67  528.01   36.74  527.16    39.8  526.63
   42.86  525.16   45.92  521.88   48.98  519.84   58.02  516.23   60.95  515.45
   63.87  514.94   66.79  514.72   69.71  514.96   72.63  515.75   75.55   517.1
    81.4  521.23   84.32  523.03   87.24  524.25   93.08  527.78   98.93  531.93
  114.03  538.72  117.05  540.95  120.07  542.59  126.12  545.14  132.16  548.28
#Mann= 3 , 0 , 0
       0      .1       0   60.95      .1       0   72.63      .1       0
Bank Sta=60.95,72.63
XS Rating Curve= 0 ,0
Exp/Cntr=0.3,0.1

Type RM Length L Ch R = 1 ,182.88  ,99.08,91.71,84.36
XS GIS Cut Line= 3
     616767.3679    4326407.8045     616844.4905     4326366.277
     616882.4298    4326359.4773
#Sta/Elev= 30
       0  547.81    9.06   539.7   12.08  537.26    15.1  535.05   18.12     532
   21.14  530.36   24.16  528.96    30.2  527.11   36.25  525.63   39.27   524.2
   42.29  519.46   45.31  516.39   48.33  514.13   51.35  512.88   54.37  512.77
   57.39  513.31   60.41  514.21   63.43  514.95   66.45  516.47   72.49  519.91
   75.51  521.46   81.55  524.07   87.59  526.87   90.56  529.28   93.52  530.97
  108.35  538.62  114.28  543.22  120.21   546.1  123.17  547.24  126.14   548.1
#Mann= 3 , 0 , 0
       0      .1       0   48.33      .1       0   60.41      .1       0
Bank Sta=48.33,60.41
XS Rating Curve= 0 ,0
Exp/Cntr=0.3,0.1

Type RM Length L Ch R = 1 ,91.1701 ,29.24,91.17,35.93
XS GIS Cut Line= 3
     616795.7615    4326481.2441       616854.35    4326475.1994
     616909.9465    4326401.8107
#Sta/Elev= 30
       0  550.07    8.83  545.08   14.72  542.06   17.67  539.77   23.56  536.18
   35.34  528.38   38.28  527.04   53.01  521.32    58.9  519.73   61.97  519.33
   68.11  516.97    79.1  513.16   83.45  511.45   86.52  510.45   89.59  510.12
   92.66  510.95   95.73  513.49    98.8   514.9  101.87  517.32  104.93  519.27
  114.14  527.76  117.21  530.21  120.28  532.38  123.35  534.42  132.56  539.96
  135.62  541.98  138.69   544.6  141.76  545.64   147.9   549.7  150.97  551.45
#Mann= 3 , 0 , 0
       0      .1       0    79.1      .1       0   95.73      .1       0
Bank Sta=79.1,95.73
XS Rating Curve= 0 ,0
Exp/Cntr=0.3,0.1
LCMann Table=0

Chan Stop Cuts=-1
Use User Specified Reach Order=0
Composite Channel Slope=5